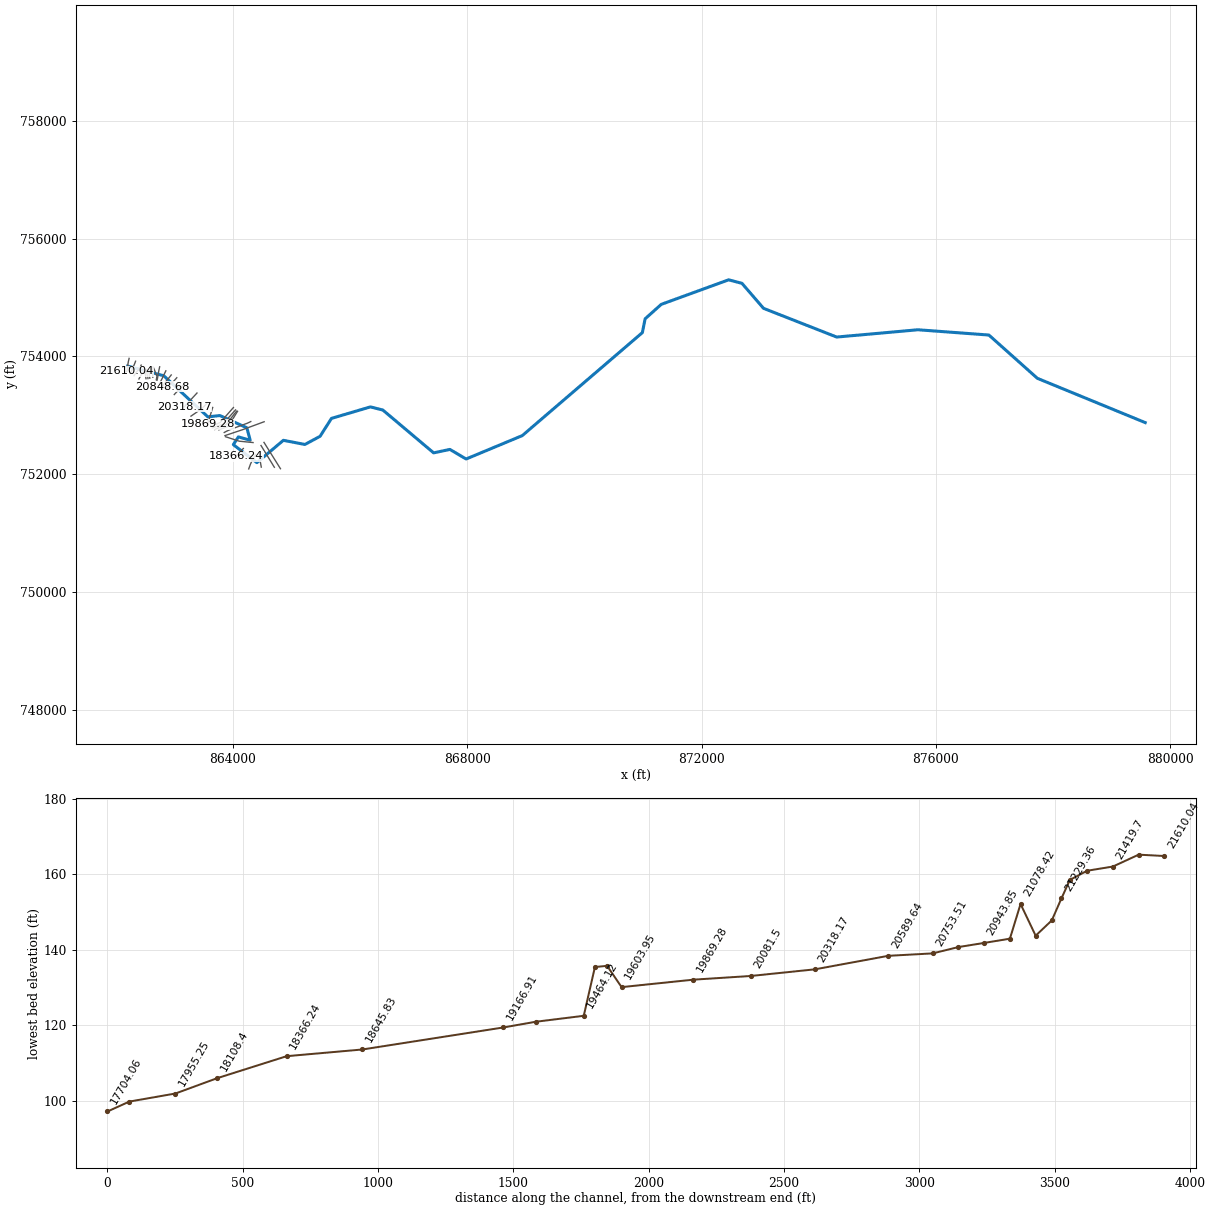
--- 9102_ras.prj (project) ---

Proj Title=9102
Current Plan=p01
Default Exp/Contr=0.3,0.1
English Units
Geom File=g01
Flow File=f01
Plan File=p01
Y Axis Title=Elevation
X Axis Title(PF)=Main Channel Distance
X Axis Title(XS)=Station
BEGIN DESCRIPTION:
RFD model 9102 exported to HEC-RAS
END DESCRIPTION:

--- 9102_ras.p01 (plan) ---

Plan Title=Plan 01
Program Version=4.10
Short Identifier=Plan 01
Geom File=g01
Flow File=f01
Subcritical Flow
Calc Critical at every XS
Secant Critical Depth

--- 9102_ras.f01 (steady flow) ---

Flow Title=Flow 01
Program Version=5.01
Number of Profiles= 6
Profile Names=10yr,25yr,50yr,100yr,100plus,500yr
River Rch & RM=9102,61,21610.04
  293.74  458.33  608.95  741.59 1082.72 1693.95
River Rch & RM=9102,61,21514.87
  512.78  801.75 1067.17 1300.65 1898.95  2747.4
River Rch & RM=9102,61, 21419.7
  514.57  804.57 1070.95 1305.29 1905.72 2755.89
River Rch & RM=9102,61,21324.53
  516.01  806.83 1073.98 1308.99 1911.13 2762.68
River Rch & RM=9102,61,21229.36
   517.8  809.66 1077.76 1313.62 1917.89 2771.15
River Rch & RM=9102,61,21078.42
  551.54  862.89  1149.1 1400.96  2045.4 2930.24
River Rch & RM=9102,61,20848.68
  552.95  865.12 1152.08 1404.61 2050.74 2936.87
River Rch & RM=9102,61,20753.51
  561.04  877.88 1169.19 1425.57 2081.33 2974.84
River Rch & RM=9102,61,20589.64
  566.96  887.25 1181.77 1440.98 2103.83 3002.78
River Rch & RM=9102,61,20318.17
  624.94  979.04 1305.05 1592.21 2324.63 3275.31
River Rch & RM=9102,61, 20081.5
  631.03  988.69 1318.02 1608.14 2347.88  3303.8
River Rch & RM=9102,61,19869.28
  633.06   991.9 1322.34 1613.44 2355.62 3313.28
River Rch & RM=9102,61,19603.95
  652.65 1022.92 1364.01 1664.55 2430.24 3404.35
River Rch & RM=9102,61,19550.42
     655 1026.64 1369.01 1670.69  2439.2 3415.27
River Rch & RM=9102,61, 19286.6
  657.02 1029.83  1373.3 1675.95 2446.88 3424.63
River Rch & RM=9102,61,19166.91
  696.98 1093.17 1458.44 1780.45 2599.46 3609.67
River Rch & RM=9102,61,18366.24
  704.58 1105.22 1474.64 1800.34 2628.49 3644.71
River Rch & RM=9102,61, 18108.4
  838.69 1317.98 1760.88 2151.86 3141.71 4256.24
River Rch & RM=9102,61,17955.25
  849.18 1334.61 1783.26 2179.33 3181.82 4303.35
River Rch & RM=9102,61,17784.93
  855.52 1344.67 1796.79 2195.94 3206.08 4331.81
River Rch & RM=9102,61,17575.05
  857.74 1348.19 1801.53 2201.76 3214.56 4341.75
River Rch & RM=9102,61,17173.23
  863.76 1357.74 1814.37 2217.52 3237.57 4368.69
River Rch & RM=9102,61,16970.89
  866.61 1362.26 1820.44 2224.97 3248.46 4381.42
River Rch & RM=9102,61,16746.91
  867.56 1363.76 1822.47 2227.46 3252.09 4385.67
River Rch & RM=9102,61,16559.47
 1016.67 1600.17 2140.45 2617.75 3821.92  5044.1
River Rch & RM=9102,61,16268.34
 1069.06 1683.26 2252.24    2755  4022.3 5272.29
River Rch & RM=9102,61,15789.77
  1077.2 1696.18 2269.65 2776.38 4053.52 5307.76
River Rch & RM=9102,61, 15311.2
 1140.22 1796.22 2404.32 2941.76 4294.98 5580.53
River Rch & RM=9102,61,14832.63
 1166.28 1837.64 2460.14 3010.37 4395.14 5693.28
River Rch & RM=9102,61,14556.08
 1180.41 1860.11 2490.43 3047.62 4449.53 5754.41
River Rch & RM=9102,61, 14302.4
 1188.34 1872.72 2507.44 3068.54 4480.06 5788.68
River Rch & RM=9102,61,13995.07
 1195.32 1883.86 2522.47 3087.04 4507.08 5819.08
River Rch & RM=9102,61,13818.13
 1199.92 1891.21 2532.42 3099.31 4524.99 5839.31
River Rch & RM=9102,61,13368.92
 1206.49 1901.73 2546.67  3116.9 4550.67 5868.35
River Rch & RM=9102,61,12970.21
  1398.9 2207.86 2959.49 3624.53 5291.81 6688.86
River Rch & RM=9102,61,12157.91
 1410.99 2227.26 2985.79 3657.04 5339.28 6741.49
River Rch & RM=9102,61,11568.57
 1992.55 3159.47 4249.27 5217.26  7617.2 9193.16
River Rch & RM=9102,61,11120.49
  2123.6 3369.83 4534.71 5569.99 8132.18 9732.58
River Rch & RM=9102,61,10701.24
 2142.19 3400.04    4576 5621.36 8207.18 9812.06
River Rch & RM=9102,61,10224.34
 2152.22 3416.37 4598.37 5649.23 8247.88 9855.31
River Rch & RM=9102,61,9946.517
 3034.47 4825.96 6505.67 7999.3411679.0413306.63
River Rch & RM=9102,61,9757.272
 3038.42 4832.43 6514.54 8010.4311695.2313323.09
River Rch & RM=9102,61,9384.879
 3042.15 4838.53 6522.93  8020.911710.5213338.62
River Rch & RM=9102,61,8413.583
 3149.74 5014.41 6764.44  8322.412150.7113784.24
River Rch & RM=9102,61,7007.794
 3272.89 5216.57 7042.78 8670.6612659.1714299.02
River Rch & RM=9102,61,6391.801
 3279.56 5227.59 7058.02  8689.812687.1114327.46
River Rch & RM=9102,61,5906.375
 3287.34 5240.51 7075.93 8712.3512720.0314361.19
River Rch & RM=9102,61,4960.759
 3633.58 5810.84 7862.96 9699.04 14160.615809.66
River Rch & RM=9102,61,3981.259
 3654.56 5845.88 7911.72 9760.6314250.5315900.99
River Rch & RM=9102,61, 2791.11
 3845.24 6163.16 8352.3710316.17 15061.616717.29
River Rch & RM=9102,61, 1586.56
 3849.02 6169.51 8361.2510327.4315078.0416734.01
River Rch & RM=9102,61,       0
 4230.42 6806.33  9247.7 11447.216712.92 18367.9
Boundary for River Rch & Prof#=9102,61,1
Up Type= 0
Dn Type= 2
Boundary for River Rch & Prof#=9102,61,2
Up Type= 0
Dn Type= 2
Boundary for River Rch & Prof#=9102,61,2
Up Type= 0
Dn Type= 2
Boundary for River Rch & Prof#=9102,61,2
Up Type= 0
Dn Type= 2
Boundary for River Rch & Prof#=9102,61,2
Up Type= 0
Dn Type= 2
Boundary for River Rch & Prof#=9102,61,2
Up Type= 0
Dn Type= 2

--- 9102_ras.g01 (geometry) ---

Geom Title=9102
Program Version=4.10

River Reach=9102,61
Reach XY= 30
862203.287436869753836.104356895862819.954103531753671.521023583
863572.871425502752972.941205579863777.245770206752996.000190208
864237.662436858752788.187690269864294.954103526752576.208523571
864093.391603524752633.500190257864006.933270187752501.729356906
864409.016603541752196.000190246864861.099936855752575.166856949
865228.808270184752504.854356865865488.183270198752643.916856923
865681.933270182752947.562690228866347.037436862753142.875190238
866558.632082409753089.545835503867425.683270193752362.146023649
867703.025400105752420.695400384867980.370770189752257.979356907
868939.224936871752655.375190231870988.303035392754404.557813087
871035.383086256754638.519216131871310.220564946754883.914602846
872461.099936867755300.861301305872688.327786428755241.248008819
873056.021818133754816.943107993874305.006565634754329.000280851
 875692.21072105754452.726540076876902.698905485754363.190779802
877730.197159092753628.118245848879570.474936881752876.382134703

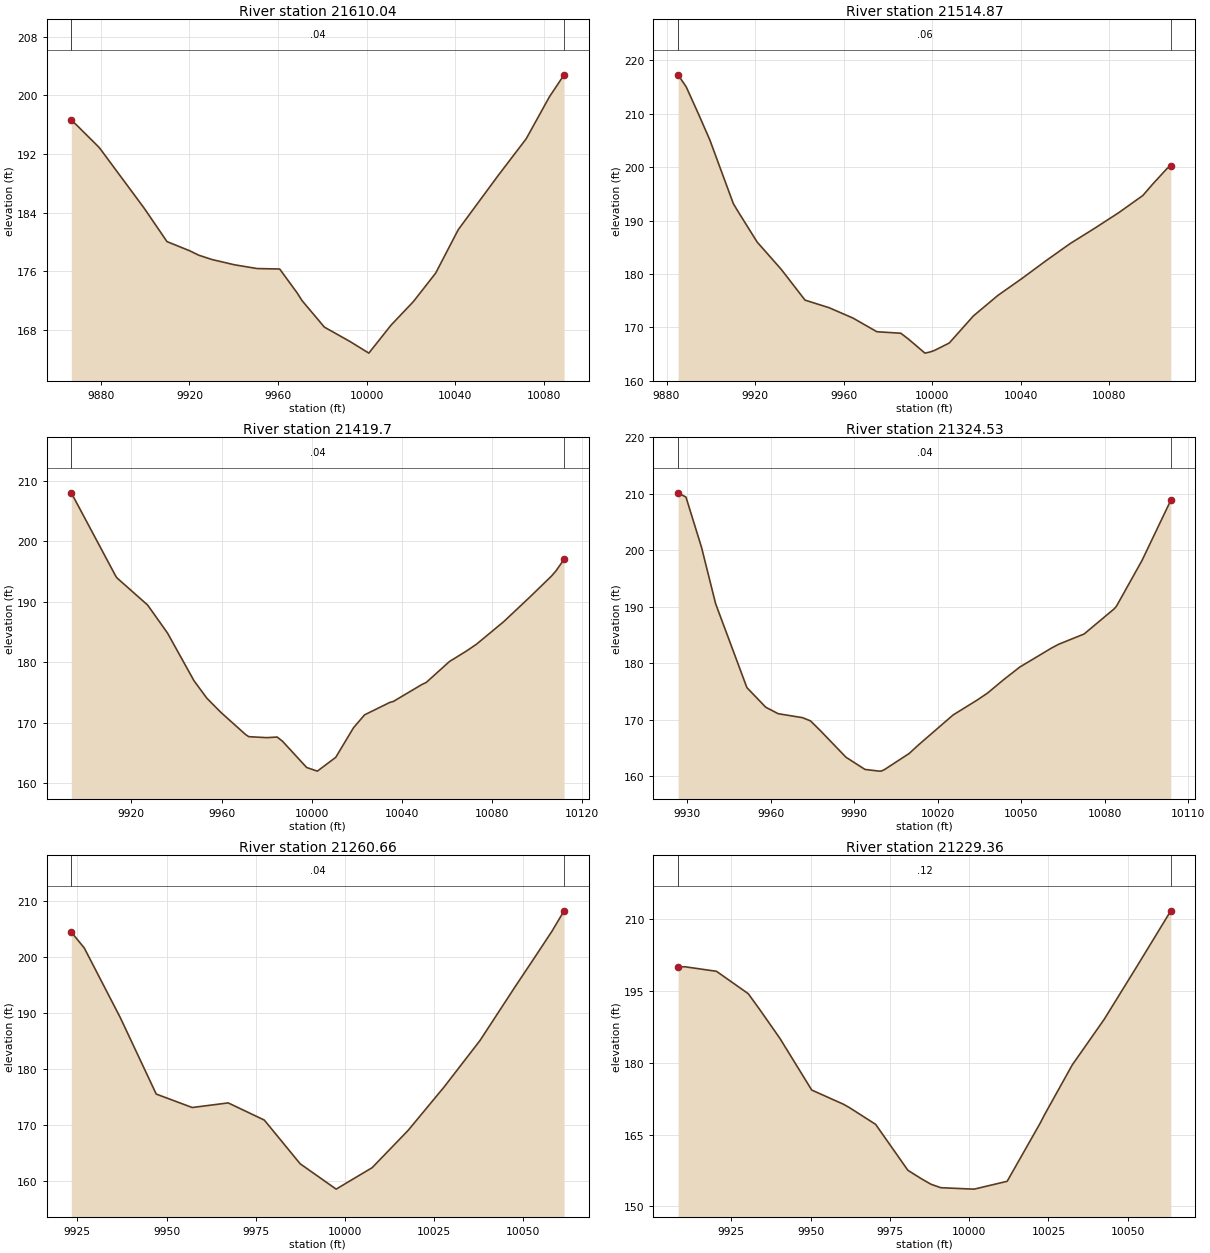
Type RM Length L Ch R = 1 ,21610.04,95.169600,95.169600,95.169600
XS GIS Cut Line= 6
862228.059724647753967.072882619862215.636561789753914.551152047
862207.275400516753867.314733601862200.843872447753804.762605725
862192.204050637753764.344936571862187.244585267753748.668160885
#Sta/Elev= 25
9866.615196.58029868.745196.03369879.021192.94719879.907192.61219899.573184.5902
9909.849180.04499920.124178.79079924.238178.18419930.285177.59149940.441176.8746
9950.596176.36749960.752176.30439968.556173.07989970.882171.98139980.927168.3793
 9992.43166.426610001.02164.826510011.08168.655210021.14171.8576 10031.2 175.742
10041.42181.6762 10059.4 189.047 10072.1194.076410082.57199.791610089.21202.8044
#Mann= 3 , 0 , 0
9866.615    0.04       09866.615    0.04       010089.21    0.04       0
#XS Ineff= 2 , 0
       0                               0
Bank Sta=9866.615,10089.21
Exp/Cntr=0.3,0.1

Type RM Length L Ch R = 1 ,21514.87,95.169600,95.169600,95.169600
XS GIS Cut Line= 6
862338.137805032753918.457790414 862328.94661889753893.088744361
862299.677886815753821.776695096862295.718233171753812.920010341
862294.864220561753811.111513043862251.723306116753713.445670688
#Sta/Elev= 29
9885.231217.27079888.909215.01649894.443209.94139899.545205.11479910.181193.1739
9912.214191.76129920.957185.96789931.767180.89149942.576175.10399953.386173.6932
9964.195171.75359975.005169.19179985.814168.90969989.298167.80529996.722165.1855
    9999165.3984   10001165.684810007.68167.073910018.61172.148210029.55175.9503
10040.48179.141510051.41182.487610062.34185.701510073.27188.525110084.21191.4644
10095.14194.692410099.66196.855310106.07199.743610107.77200.2687
#Mann= 3 , 0 , 0
9885.231    0.06       09885.231    0.06       010107.77    0.06       0
#XS Ineff= 2 , 0
       0                               0
Bank Sta=9885.231,10107.77
Exp/Cntr=0.3,0.1

Type RM Length L Ch R = 1 , 21419.7,95.169500,95.169500,95.169500
XS GIS Cut Line= 6
862434.377342777753852.563929863862418.777994118753822.494712431
862404.496865302753799.332852686 862389.48377754753778.514278607
862345.444501627 753724.23088243862312.177775849753671.956010695
#Sta/Elev= 30
9893.344208.02839913.123194.22379913.743193.92419927.221189.48099936.026184.8597
9947.774176.98349953.473174.09449959.773171.72939970.668168.08669972.102 167.731
9980.099  167.579984.696167.66919987.053166.97859997.778162.635510002.53162.0371
10010.69164.317410018.59169.220510023.47171.337410034.66 173.38910036.25173.5526
10049.03 176.37910050.81 176.68310061.11180.143310068.83181.921510073.13183.0117
10085.15186.720110096.85190.817510106.44 194.28510108.46195.155510111.99197.0438
#Mann= 3 , 0 , 0
9893.344    0.04       09893.344    0.04       010111.99    0.04       0
#XS Ineff= 2 , 0
       0                               0
Bank Sta=9893.344,10111.99
Exp/Cntr=0.3,0.1

Type RM Length L Ch R = 1 ,21324.53,63.874800,63.874800,63.874800
XS GIS Cut Line= 6
 862487.84919609753767.677671467862483.430375793753755.380008431
862468.985802948  753727.2591921862429.727405928753678.128229107
862399.950168176753627.021983856862395.489913857753617.667166782
#Sta/Elev= 29
9926.676210.17659929.521209.41379935.102200.5329 9940.17190.55459951.413175.7014
9958.194172.23259962.655171.09039971.357170.3923 9974.24169.82789977.772168.1148
9987.002163.39199993.868161.2233    9999160.92779999.812160.9509   10001161.2473
10009.76164.062810012.67165.389710025.46170.847610034.25173.530110037.87174.7346
10043.64177.098610049.45179.336110061.02182.7481 10063.5183.389410072.59185.1937
10083.37189.634810084.17190.0735 10093.4198.207910103.76208.8735
#Mann= 3 , 0 , 0
9926.676    0.04       09926.676    0.04       010103.76    0.04       0
#XS Ineff= 2 , 0
       0                               0
Bank Sta=9926.676,10103.76
Exp/Cntr=0.3,0.1

Type RM Length L Ch R = 1 ,21260.66,31.294800,31.294800,31.294800
XS GIS Cut Line= 2
862497.631590991753758.602844463 862516.23396246753621.661594373
#Sta/Elev= 18
9923.302204.37019926.938201.5415 9937.03189.12739947.122175.46459957.213173.0652
9967.305173.88649977.397170.83569978.043170.35069987.489163.02319997.581158.4976
10007.67162.324610017.76168.977110027.86176.732810037.95185.047510048.04194.8819
10052.33 198.96410058.13204.5531 10061.5 208.171
#Mann= 3 , 0 , 0
9923.302    0.04       09923.302    0.04       0 10061.5    0.04       0
#XS Ineff= 2 , 0
       0                               0
Bank Sta=9923.302,10061.5
Exp/Cntr=0.3,0.1

Type RM Length L Ch R = 1 ,21229.36,35.563400,35.563400,35.563400
XS GIS Cut Line= 6
 862530.15618601753777.081818229862528.479817337753751.536806949
862529.822390074753723.164246722862534.044944166753700.941695866
862545.365781873753663.668636143862550.120708745753624.144312036
#Sta/Elev= 27
9908.179200.00839910.265200.08769920.286199.13619930.308194.45629933.778191.2848
9940.323185.08269950.334174.30149960.345171.33159962.183170.64789970.493167.1242
9980.672157.51519984.803155.79989987.937154.60599991.041153.8813    9999 153.646
   10001153.594510001.58153.580110011.98155.217310022.38167.357610022.44167.4329
10023.77169.145510032.51179.5504 10042.6189.103110052.69199.923510060.06207.9284
10062.75210.864810063.61211.7796
#Mann= 3 , 0 , 0
9908.179    0.12       09908.179    0.12       010063.61    0.12       0
#XS Ineff= 2 , 0
       0                               0
Bank Sta=9908.179,10063.61
Exp/Cntr=0.3,0.1

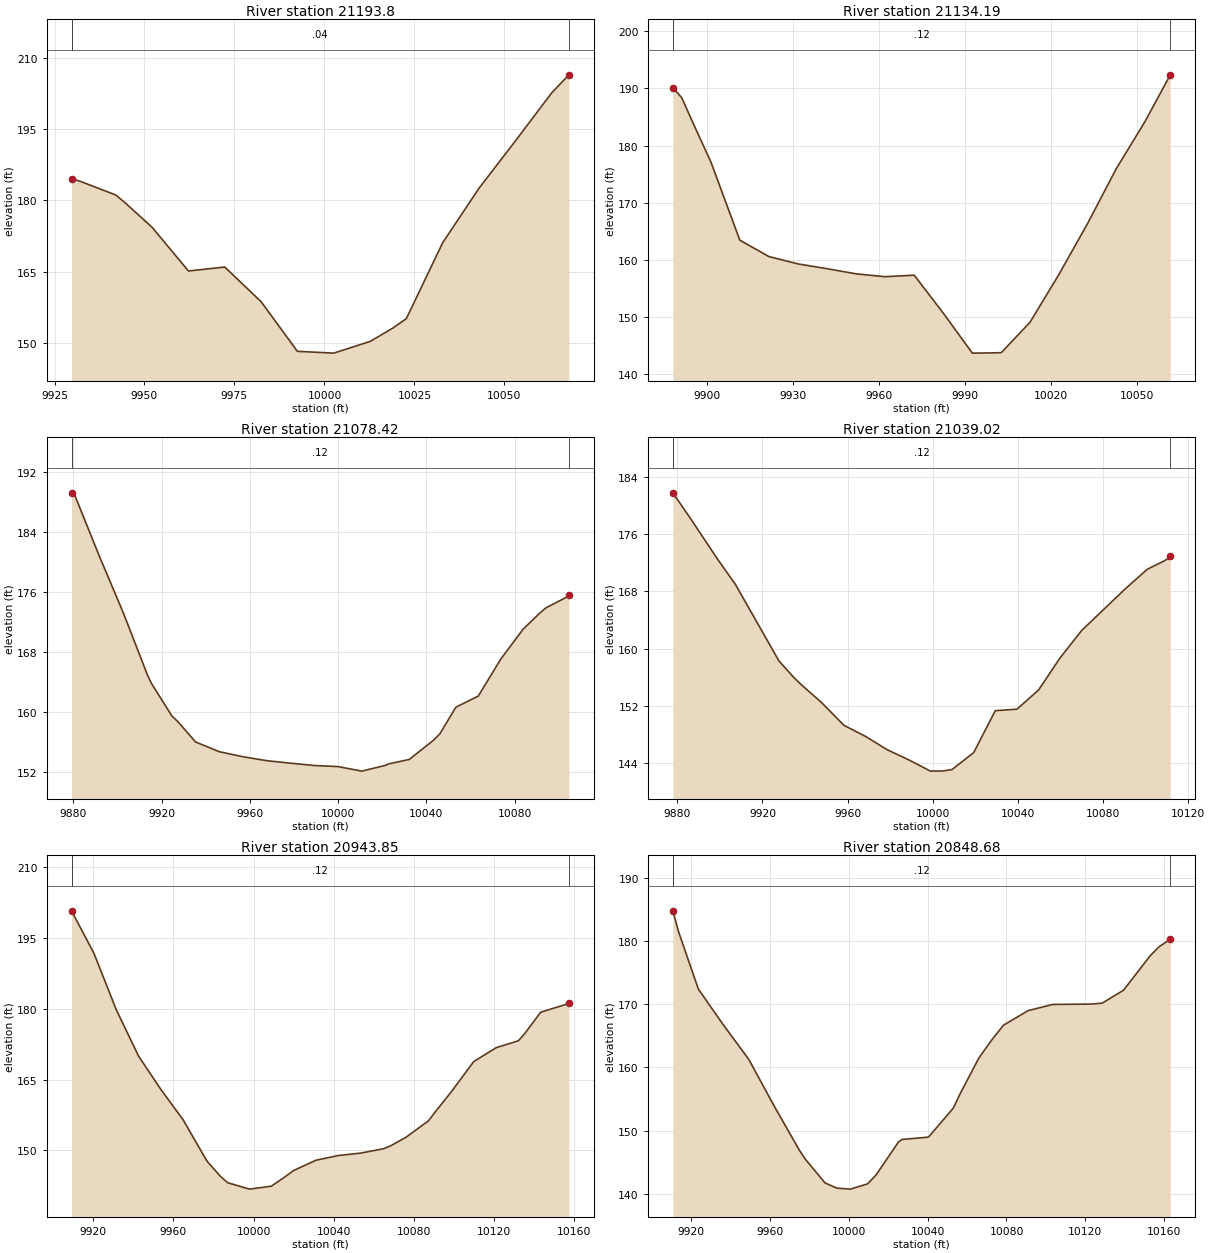
Type RM Length L Ch R = 1 , 21193.8,59.606200,59.606200,59.606200
XS GIS Cut Line= 2
862562.972510215753767.182647388 862581.57502001753630.241434196
#Sta/Elev= 18
9929.729184.59959931.932184.11179942.024181.15999944.791179.39569952.115 174.336
9962.207 165.1089972.299165.94439982.391  158.649992.483148.143810002.57147.7645
10012.67150.227610019.08153.090510022.76155.059510032.85171.084410042.94182.5891
10053.03192.553610063.13202.726910067.93206.5375
#Mann= 3 , 0 , 0
9929.729    0.04       09929.729    0.04       010067.93    0.04       0
#XS Ineff= 2 , 0
       0                               0
Bank Sta=9929.729,10067.93
Exp/Cntr=0.3,0.1

Type RM Length L Ch R = 1 ,21134.19,55.777000,55.777000,55.777000
XS GIS Cut Line= 4
862613.814817182753818.046411301862630.930214964753708.635428911
862631.032644459753706.638053478862632.392997951753646.155925094
#Sta/Elev= 23
9888.258190.11519891.342188.38389895.927183.24089901.463177.18899911.585163.4705
9921.707160.60969931.828159.3275 9941.95158.48939952.072157.5892 9960.63157.1645
9962.193157.09039972.315157.35359982.436150.71969992.558 143.728    9999143.7669
   10001143.790210002.64143.812610012.64149.126610022.64157.424310032.65166.3469
10042.65175.940210052.65184.1814 10061.5192.3833
#Mann= 3 , 0 , 0
9888.258    0.12       09888.258    0.12       0 10061.5    0.12       0
#XS Ineff= 2 , 0
       09967.427        10023.18       0
Bank Sta=9888.258,10061.5
Exp/Cntr=0.3,0.1

Type RM Length L Ch R = 1 ,21078.42,39.392600,39.392600,39.392600
XS GIS Cut Line= 4
862640.231464938753816.491446096 862659.90245711753772.414002521
862703.633473341753662.134410974862692.471338008753604.672279893
#Sta/Elev= 29
9879.155189.21789880.789188.78189891.739180.7902 9902.69173.1709 9913.64164.8718
9915.394163.80739924.591159.49729927.423158.69069935.399156.00289946.156154.7074
9956.914154.03519967.671153.51239978.429153.17699989.186152.87189999.944152.7276
 10010.7152.121310021.46152.891610022.64153.071310032.22153.678910042.97156.1863
10046.06157.083610053.32160.637610063.51162.1315 10073.7167.058310083.89171.0687
10091.33173.179510094.07173.865510104.26175.426410104.59175.5574
#Mann= 3 , 0 , 0
9879.155    0.12       09879.155    0.12       010104.59    0.12       0
#XS Ineff= 2 , 0
       09953.895        10036.68       0
Bank Sta=9879.155,10104.59
Exp/Cntr=0.3,0.1

Type RM Length L Ch R = 1 ,21039.02,95.169500,95.169500,95.169500
XS GIS Cut Line= 6
862749.575793431753823.648338481862737.251683684753768.366878078
862726.056495138 753704.90159121862725.646768834753702.944009975
862712.126955575 753625.15164437862704.218340335 753594.55379499
#Sta/Elev= 26
9877.916181.74559886.777177.91149898.946172.47919907.268168.98439927.759158.2938
9934.555156.04799937.974155.05019947.517152.56379958.283149.31749968.437147.7728
9978.591145.91289988.746 144.498  9998.9142.929910004.78 142.95210009.06143.1559
10019.21145.513610029.36151.362710039.51151.568410049.66154.233310059.81158.7359
10069.96162.556810090.44168.362410100.77171.088410108.44172.2144 10111.1172.6843
10111.56172.8933
#Mann= 3 , 0 , 0
9877.916    0.12       09877.916    0.12       010111.56    0.12       0
#XS Ineff= 2 , 0
       09960.539        10043.17       0
Bank Sta=9877.916,10111.56
Exp/Cntr=0.3,0.1

Type RM Length L Ch R = 1 ,20943.85,95.169600,95.169600,95.169600
XS GIS Cut Line= 6
862854.963926886753755.027570102862822.279404212753688.311386423
862815.318298997753672.203348528862809.549305388753659.229103678
862763.162568163753569.040100408862745.294102736753532.287834103
#Sta/Elev= 29
9909.158200.71179920.324191.74579931.459179.81749942.595169.9841 9953.73162.9237
9964.866156.48629976.002148.28699977.266147.4823 9983.45144.53639987.067143.1727
9997.989141.808310008.88142.4309 10015.2144.249210019.95145.7332 10031.2147.9256
10042.45148.931610053.69149.440610064.94150.363310068.87151.066110076.18152.8054
10087.43156.292810090.74158.153510098.67 162.36810109.92168.793110121.11171.7384
10132.23173.210710135.29174.656610143.35179.245610157.48181.1061
#Mann= 3 , 0 , 0
9909.158    0.12       09909.158    0.12       010157.48    0.12       0
#XS Ineff= 2 , 0
       0                               0
Bank Sta=9909.158,10157.48
Exp/Cntr=0.3,0.1

Type RM Length L Ch R = 1 ,20848.68,95.169600,95.169600,95.169600
XS GIS Cut Line= 6
862946.651138891753685.440380708862936.370843476753671.319343552
862891.832640612753616.447236283862848.705634904753564.828869006
862804.072673402753505.019262842862791.869326005753486.515166102
#Sta/Elev= 30
9910.861 184.8099913.666181.57739923.775172.40979936.467 166.7329949.346161.2719
9962.238 153.8649975.105146.82189978.106  145.429987.984141.70449993.974140.8718
10000.91140.711910009.62141.552510013.94142.980510025.23148.181910026.96148.5842
10039.99148.934910040.83149.090610053.02153.542210056.44  155.7910066.04161.5098
10072.46164.323110078.53166.697210091.01168.999310103.48 169.97710122.62170.0336
10128.44170.170110139.34172.225810152.89177.704410157.37179.120610163.06180.3073
#Mann= 3 , 0 , 0
9910.861    0.12       09910.861    0.12       010163.06    0.12       0
#XS Ineff= 2 , 0
       0                               0
Bank Sta=9910.861,10163.06
Exp/Cntr=0.3,0.1

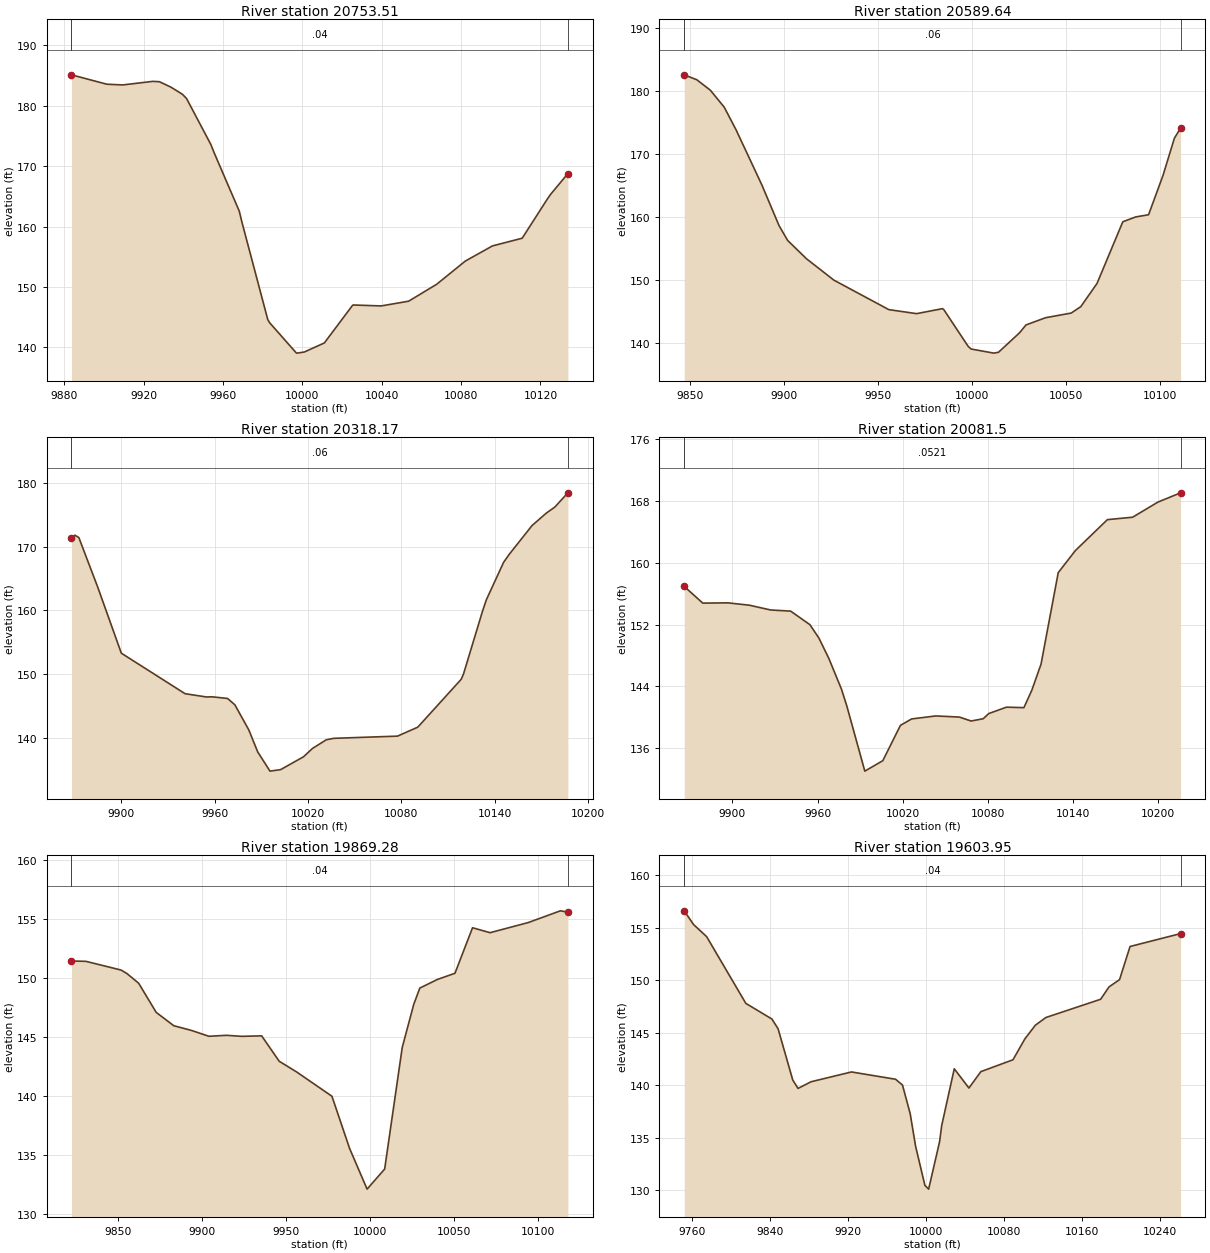
Type RM Length L Ch R = 1 ,20753.51,163.877100,163.877100,163.877100
XS GIS Cut Line= 6
863041.981288104753638.391082499863009.010018623753600.640019084
 862963.53736739753553.831139948862962.123153828753552.416926367
862906.361273131753496.500555363862867.759951525753458.935042531
#Sta/Elev= 29
9883.618185.11269901.397183.56099909.433183.43929924.634184.03089927.951183.9695
 9933.74183.07569939.495181.90179941.603181.19959953.847173.59479955.545172.2013
9968.198162.54199969.487160.78059982.549144.60399983.429144.09859996.901139.0808
 9997.37139.0377   10001139.225810011.09140.725110025.25146.9336 10025.6147.0079
10039.72146.850910053.57147.635610067.73150.444710082.12154.276610095.82156.7898
 10110.8158.062510123.73164.675910125.14165.331110133.83168.7652
#Mann= 3 , 0 , 0
9883.618    0.04       09883.618    0.04       010133.83    0.04       0
#XS Ineff= 2 , 0
       0                               0
Bank Sta=9883.618,10133.83
Exp/Cntr=0.3,0.1

Type RM Length L Ch R = 1 ,20589.64,271.462200,271.462200,271.462200
XS GIS Cut Line= 2
863179.581327707753545.144130716862998.627108956753352.588234629
#Sta/Elev= 30
9846.947182.59719853.637  181.829860.867180.15539868.239177.4678 9874.59173.8426
9888.313165.09439897.444158.64489902.035156.28519912.047153.38359926.649149.9822
9955.854145.30639970.649144.66429984.372145.45539985.059145.33779998.094139.4777
9999.662139.046510011.82138.394310014.26 138.53110025.54141.645510028.87142.8671
10039.26144.013610052.99144.760710058.07145.780610066.71149.463410080.43159.2559
10087.28160.025610094.15160.374610101.88166.662910107.88172.527810111.19174.1397
#Mann= 3 , 0 , 0
9846.947    0.06       09846.947    0.06       010111.19    0.06       0
#XS Ineff= 2 , 0
       0 9974.67                       0
Bank Sta=9846.947,10111.19
Exp/Cntr=0.3,0.1

Type RM Length L Ch R = 1 ,20318.17,236.678000,236.678000,236.678000
XS GIS Cut Line= 2
863386.466012285753378.462103319863169.329542235753144.768540525
#Sta/Elev= 30
9868.031171.33089870.185171.78549872.757171.41989884.876163.66349900.058153.2988
9941.009146.94889954.659146.43649958.332 146.4599968.309146.20289973.023145.2095
 9981.96141.28429987.715137.8204 9995.61134.812810002.41135.0458 10017.1137.0556
10022.91138.366610031.79139.728210036.56139.952510077.51140.297510090.55141.6995
10118.46149.199310119.94150.022710132.11159.826910134.63161.662110145.76167.5498
10149.32168.784910164.01173.300210173.06175.2287 10178.7176.208510187.03178.4275
#Mann= 3 , 0 , 0
9868.031    0.06       09868.031    0.06       010187.03    0.06       0
#XS Ineff= 2 , 0
       09966.337                       0
Bank Sta=9868.031,10187.03
Exp/Cntr=0.3,0.1

Type RM Length L Ch R = 1 , 20081.5,212.217900,212.217900,212.217900
XS GIS Cut Line= 6
 863553.53885382753205.432507701863532.531962436753177.707921499
863510.111639244753153.075041715 863487.02453742 753132.00100727
863379.346562573 753051.06752779863283.747936316752985.987977513
#Sta/Elev= 30
9866.027156.93019879.116154.76899896.725154.80449912.001154.49819926.857153.8833
9941.041 153.735 9954.58151.9856 9960.93150.25599967.943147.61519976.782143.6708
9980.612141.4674 9993.28133.055810005.95134.404510018.39138.975710026.27139.7993
10043.28140.188810059.87140.042810068.17139.533310076.68139.827610080.61140.4977
10093.05141.320410105.35141.262210110.87143.483910117.44146.891210129.54158.7077
10141.64161.567210164.18165.557910181.95165.871510199.72167.822110215.74169.0236
#Mann= 3 , 0 , 0
9866.027  0.0521       09866.027  0.0521       010215.74  0.0521       0
#XS Ineff= 2 , 0
       0                               0
Bank Sta=9866.027,10215.74
Exp/Cntr=0.3,0.1

Type RM Length L Ch R = 1 ,19869.28,265.325700,265.325700,265.325700
XS GIS Cut Line= 2
863654.685515014753133.224351181863568.117505514752850.731938001
#Sta/Elev= 28
9822.075151.42519830.677151.39539851.595 150.6579855.132150.35499862.054149.5402
9872.513147.06519882.972145.93499893.431145.5377 9903.89145.04049914.349145.1219
9923.393 145.0359935.267145.07569945.726142.91919956.185142.00549977.103139.9537
9987.562135.54539998.021132.076610008.48 133.78210018.94144.092410025.78147.7412
 10029.4149.126910039.86149.858810050.32150.382210060.78 154.24510071.23 153.825
10094.04154.689410113.07155.679610117.53155.5693
#Mann= 3 , 0 , 0
9822.075    0.04       09822.075    0.04       010117.53    0.04       0
#XS Ineff= 2 , 0
       0                               0
Bank Sta=9822.075,10117.53
Exp/Cntr=0.3,0.1

Type RM Length L Ch R = 1 ,19603.95,53.538000,53.538000,53.538000
XS GIS Cut Line= 3
 864008.96014185 753132.18194603863781.712364936752876.708275484
863626.956441937752814.400484047
#Sta/Elev= 30
 9752.35156.59789761.962155.29139775.346154.14179815.497147.79069842.264146.2946
9848.585145.36739863.631140.48839869.032139.69139882.415140.32669923.815141.2589
9968.953140.56499976.101140.00769983.999137.27269989.485134.19419999.046130.4578
10002.87130.103310014.09134.619310016.25136.148310029.14141.559610044.18139.7283
 10056.4141.288810089.32142.4178 10101.5144.405410112.28145.711210123.06146.4418
10179.17148.178210187.75149.356210198.53150.046810209.31153.2022 10261.1154.4308
#Mann= 3 , 0 , 0
 9752.35    0.04       0 9752.35    0.04       0 10261.1    0.04       0
#XS Ineff= 2 , 0
       09963.649        10024.69       0
Bank Sta=9752.35,10261.1
Exp/Cntr=0.3,0.1

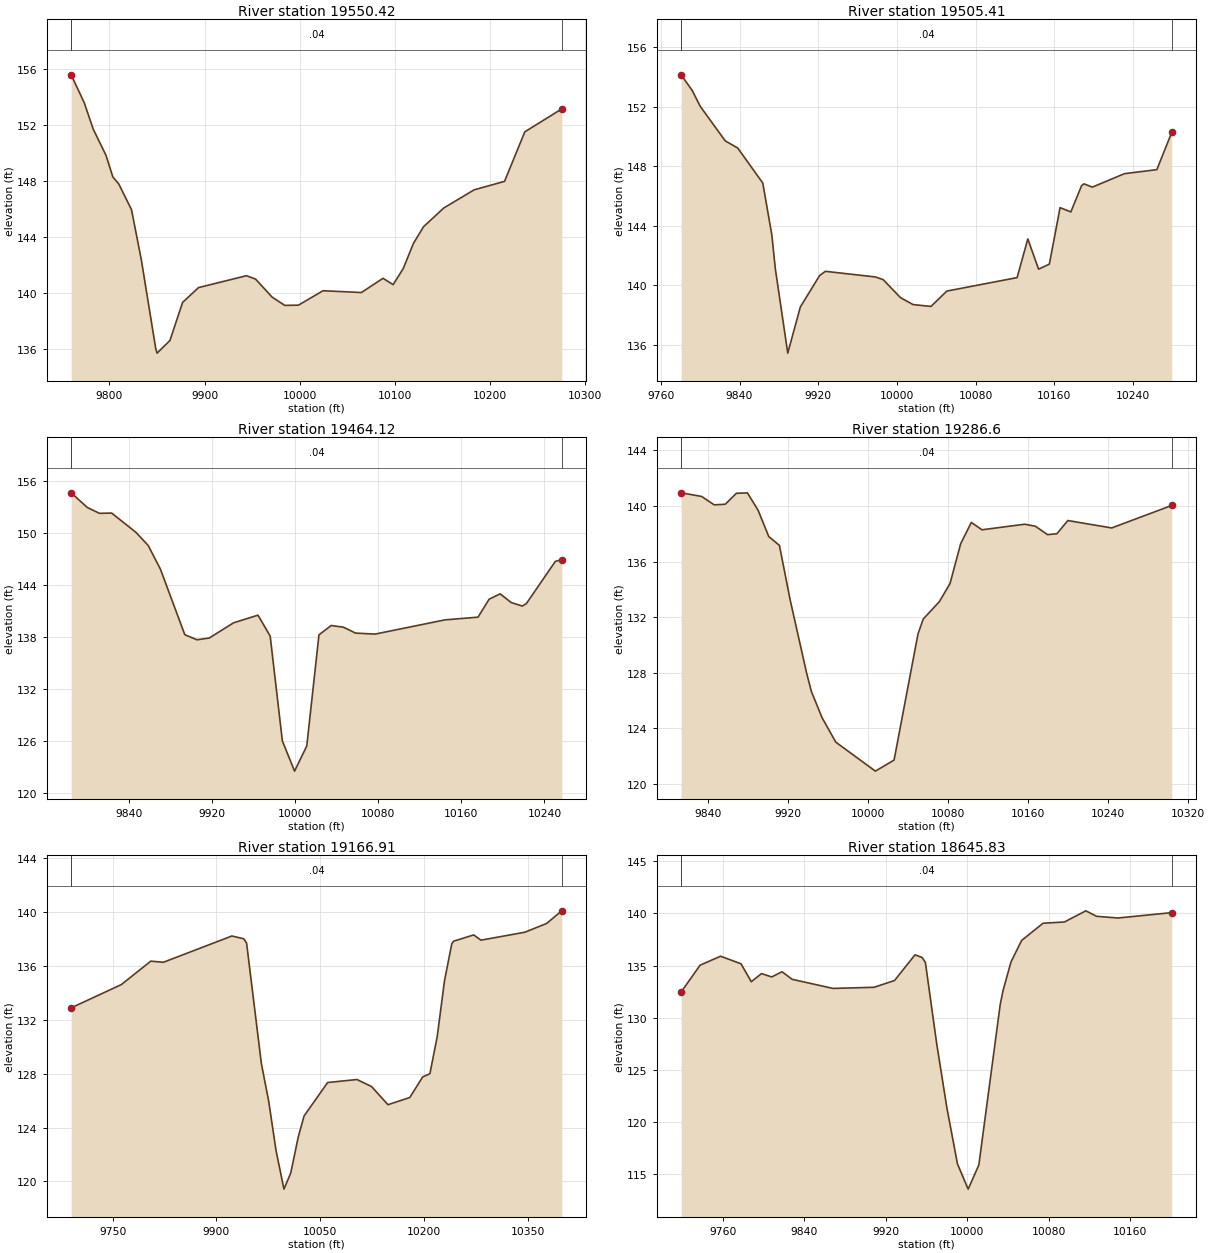
Type RM Length L Ch R = 1 ,19550.42,45.003800,45.003800,45.003800
XS GIS Cut Line= 3
864044.174919401753092.254709617863827.683194648752850.171750267
863648.512340177 752784.93711935
#Sta/Elev= 30
9759.883155.60439773.646153.60189783.031151.72899796.446149.86119803.649148.3159
9809.862147.81759823.277145.97339833.651142.36999848.653136.08819850.108 135.739
9863.654136.64299876.939139.35829893.657140.41559944.016141.26659953.662141.0221
9970.847139.74569984.263139.14569998.666139.162910024.51 140.19310064.76140.0644
 10087.5141.079810098.15140.627310108.79141.778310119.43143.564910130.07  144.76
10151.36146.098910183.28147.394910215.21147.999810236.49151.533810275.33153.1705
#Mann= 3 , 0 , 0
9759.883    0.04       09759.883    0.04       010275.33    0.04       0
#XS Ineff= 2 , 0
       09960.368         10014.1       0
Bank Sta=9759.883,10275.33
Exp/Cntr=0.3,0.1

Type RM Length L Ch R = 1 ,19505.41,41.291800,41.291800,41.291800
XS GIS Cut Line= 3
864061.997140259753070.192561522863883.933194637752843.921750262
863691.163806915752759.081450433
#Sta/Elev= 30
9780.702154.14819792.016153.08819800.035152.03659825.485149.7071 9838.21149.2244
 9863.66146.87059872.867143.37879876.385141.12219889.037135.43139901.836138.5355
9921.378140.64549927.286140.93269978.186140.55379986.059140.369510003.64139.1614
10016.36138.697210034.57138.571710050.74139.6048 10122.1140.509310133.02143.1124
10143.95141.079410154.87 141.416 10165.8145.217310176.73144.926810187.65146.6954
10190.08 146.81710198.58146.595210231.35147.503210264.13147.770310279.25150.2738
#Mann= 3 , 0 , 0
9780.702    0.04       09780.702    0.04       010279.25    0.04       0
#XS Ineff= 2 , 0
       09973.533        10021.06       0
Bank Sta=9780.702,10279.25
Exp/Cntr=0.3,0.1

Type RM Length L Ch R = 1 ,19464.12,177.522800,177.522800,177.522800
XS GIS Cut Line= 3
864078.919299925753068.167183095863920.871046526752812.307781241
863759.215988319752753.303570071
#Sta/Elev= 30
9783.905154.59379799.381152.90819811.135152.22869822.889152.26089846.398150.0288
9858.152148.51689869.906145.79229893.414138.23589905.168137.65249916.922137.8514
 9940.43139.60929963.938140.48749975.692138.07979987.446125.9805  9999.2122.5082
10010.95125.402410022.71138.219110034.46139.297110046.22 139.10610057.97138.4216
10076.79138.306510144.12139.946910176.05140.2606 10186.7142.328210197.35142.9471
10207.99141.945310218.64141.542110222.62141.826310250.57 146.69310256.73146.8837
#Mann= 3 , 0 , 0
9783.905    0.04       09783.905    0.04       010256.73    0.04       0
#XS Ineff= 2 , 0
       09967.469        10036.08       0
Bank Sta=9783.905,10256.73
Exp/Cntr=0.3,0.1

Type RM Length L Ch R = 1 , 19286.6,119.685900,119.685900,119.685900
XS GIS Cut Line= 5
  864304.7442297752893.868012121864246.234531406752865.783628886
863963.469046936752762.311459743863893.609068413752730.978121903
863851.893171951752708.401841862
#Sta/Elev= 30
 9813.47140.95289833.964140.69089846.464 140.0899857.556140.13159868.648140.9195
9879.686 140.9479890.334139.69969900.983137.80659911.631137.1694 9922.28133.2721
9938.851127.96469943.577126.65249954.225124.77229967.951123.012810007.47120.9289
10026.15121.723510050.06130.806810055.25131.866910071.36133.122110082.01134.4222
10092.66  137.29 10103.3138.824110113.95138.292410156.55138.6936 10167.2138.5509
10179.47137.944210188.76138.008110199.72 138.95910243.55138.425610303.47140.0458
#Mann= 3 , 0 , 0
 9813.47    0.04       0 9813.47    0.04       010303.47    0.04       0
#XS Ineff= 2 , 0
       0                 10106.7       0
Bank Sta=9813.47,10303.47
Exp/Cntr=0.3,0.1

Type RM Length L Ch R = 1 ,19166.91,521.085400,521.085400,521.085400
XS GIS Cut Line= 3
 864533.04227699752890.893201057864164.057490016752755.583822583
863864.207816436752655.386505677
#Sta/Elev= 30
9690.021132.89489762.494134.62289805.098 136.3659823.319136.28229922.261138.2342
9939.501138.02839943.564137.71149964.866128.77679975.517125.95459986.168122.2775
9997.592119.419610007.47120.625310018.12123.267310026.64124.856110060.73127.3436
10103.13 127.56710124.21127.044510147.98125.694510179.53126.230810198.02127.7555
10208.56127.9986 10219.1130.743710229.65134.902410240.19137.654610242.64137.8442
10271.82138.315910282.37137.925510345.63138.511710377.26139.164710399.18140.1059
#Mann= 3 , 0 , 0
9690.021    0.04       09690.021    0.04       010399.18    0.04       0
#XS Ineff= 2 , 0
       0                10063.25       0
Bank Sta=9690.021,10399.18
Exp/Cntr=0.3,0.1

Type RM Length L Ch R = 1 ,18645.83,279.585500,279.585500,279.585500
XS GIS Cut Line= 3
864343.538960509752537.098281179864108.108558788752560.631847362
863874.693642951752635.754428502
#Sta/Elev= 30
 9718.86132.47569737.491135.04559757.591135.9044 9777.69135.1767 9787.74133.4613
 9797.79134.2377 9807.84133.9175 9817.89134.4155 9827.94133.68729868.139132.8174
9908.338132.92689928.438133.57599948.538136.03739955.463135.78679958.729135.3138
9969.721127.60159979.739121.43729990.244115.998510000.75113.586610011.25115.9024
10032.26131.3002   10035132.604710042.77135.345610053.28137.417310074.29 139.063
 10095.3139.185610116.31140.253110126.81139.730310147.82139.564810200.67140.0798
#Mann= 3 , 0 , 0
 9718.86    0.04       0 9718.86    0.04       010200.67    0.04       0
#XS Ineff= 2 , 0
       0                               0
Bank Sta=9718.86,10200.67
Exp/Cntr=0.3,0.1

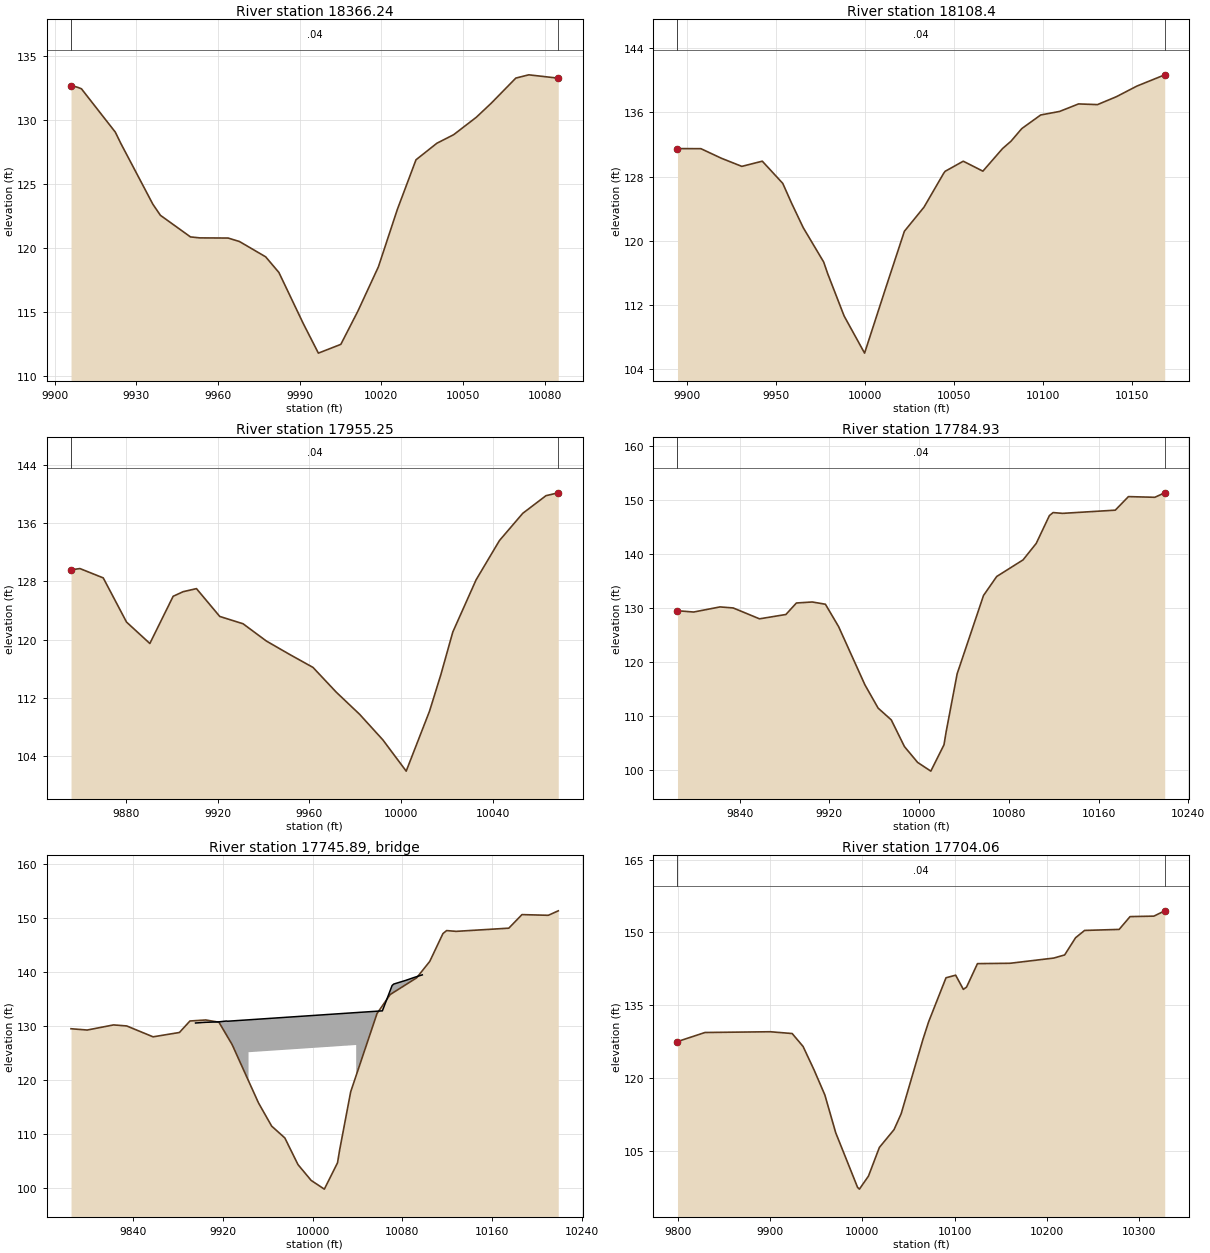
Type RM Length L Ch R = 1 ,18366.24,257.837300,257.837300,257.837300
XS GIS Cut Line= 2
 864177.63918841 752436.77613249864054.255841361752307.161876699
#Sta/Elev= 28
9906.015132.70739908.467132.56749909.843132.45229922.274129.07159924.346128.1707
 9936.08123.4378 9938.85122.57489949.886120.88789953.354120.81089963.693120.7996
9967.857120.53049977.499119.33389982.361118.11269991.306114.12729996.864111.8139
10005.11112.498710011.37115.091210018.92 118.55910025.87123.035910032.72126.9096
10040.38128.200510046.53128.866610054.88130.231210060.34131.325210069.38133.2876
10074.14133.543210083.89133.307910084.97133.2611
#Mann= 3 , 0 , 0
9906.015    0.04       09906.015    0.04       010084.97    0.04       0
#XS Ineff= 2 , 0
       0                               0
Bank Sta=9906.015,10084.97
Exp/Cntr=0.3,0.1

Type RM Length L Ch R = 1 , 18108.4,153.156100,153.156100,153.156100
XS GIS Cut Line= 6
864386.788967832752336.450638611864335.097476402752245.653146088
864334.151841004752243.890825602864329.156347263752234.460361795
864299.317911404752170.720859496 864269.61716067752089.481387606
#Sta/Elev= 29
9894.519131.48579907.696131.47519919.203130.2805 9930.71129.26689942.217129.9143
9953.724127.14449958.772124.63269965.231121.62329976.738117.33319978.985115.8835
9988.245110.59249999.741105.965410011.67114.121910022.12121.168110033.16124.1791
 10044.2128.394210045.06128.652710055.24129.911710066.28128.670910077.33 131.488
10082.05132.397210088.14133.979910098.79135.681310109.44136.122810120.08137.0585
10130.73136.974610141.38 137.96210152.87139.283210168.55  140.69
#Mann= 3 , 0 , 0
9894.519    0.04       09894.519    0.04       010168.55    0.04       0
#XS Ineff= 2 , 0
       0                               0
Bank Sta=9894.519,10168.55
Exp/Cntr=0.3,0.1

Type RM Length L Ch R = 1 ,17955.25,170.319200,170.319200,170.319200
XS GIS Cut Line= 2
864446.291196139752328.821520463864484.118295551752119.746542376
#Sta/Elev= 26
9856.052129.58489859.935129.75379870.098128.4724 9880.26122.40239890.422 119.463
9900.585125.94469904.968126.57899910.747126.99869920.909123.17669931.072122.1711
9941.234119.79889951.396117.95629961.136116.25079961.559116.17799971.721112.7724
9981.883109.73859992.046106.217710002.21101.928910012.37110.1538 10017.3115.1569
10022.53121.0367 10032.7128.214110042.86133.595710053.02 137.33810063.18139.7699
10068.52140.1576
#Mann= 3 , 0 , 0
9856.052    0.04       09856.052    0.04       010068.52    0.04       0
#XS Ineff= 2 , 0
       0                               0
Bank Sta=9856.052,10068.52
Exp/Cntr=0.3,0.1

Type RM Length L Ch R = 1 ,17784.93,80.871300,80.871300,80.871300
XS GIS Cut Line= 2
864479.406991462752487.273115125864707.184393649 752117.46229352
#Sta/Elev= 30
9784.666129.47789799.081129.2383 9822.57 130.1859834.315129.99329857.804127.9801
9881.293128.78469890.672130.90959904.783131.09869916.527130.68229928.272126.5444
9951.761115.75739963.506111.45749975.251109.26879986.995104.3268 9998.74101.3997
10010.4899.7903910022.23104.667410024.15107.074710033.97 117.81410057.46132.3011
10069.21135.8142 10092.7138.888210104.44141.937710116.19147.090610119.49147.6462
10127.93147.501810174.91148.093210186.65150.602110210.14150.4753   10219151.3029
#Mann= 3 , 0 , 0
9784.666    0.04       09784.666    0.04       0   10219    0.04       0
#XS Ineff= 2 , 0
       0                               0
Bank Sta=9784.666,10219
Exp/Cntr=0.3,0.1

Type RM Length L Ch R = 3 ,17745.89,,,
BEGIN DESCRIPTION:
END DESCRIPTION:
Bridge Culvert--1,0,-1,-1, 0
Deck Dist Width WeirC Skew NumUp NumDn MinLoCord MaxHiCord MaxSubmerge Is_Ogee
18.935650,43.000000,2.6,0, 17, 17, , , 0.95, 0, 0,0,,
 9895.66 9904.58 9904.99 9916.84 9923.22 9924.14 9942.89 9942.8910038.8910038.89
10062.2210070.8810072.3510082.7310090.9910094.5810097.80
  130.54  130.67  130.67  130.76  130.91  130.87  131.13  131.13  132.47  132.47
  132.79  137.48  137.75  138.41  139.00  139.24  139.45
 -869.46 -869.33 -869.33 -869.24 -869.09 -869.13 -868.87  125.13  126.47 -867.53
 -867.21 -862.52 -862.25 -861.59 -861.00 -860.76 -860.55
 9895.66 9904.58 9904.99 9916.84 9923.22 9924.14 9953.31 9953.3110049.3110049.31
10062.2210070.8810072.3510082.7310090.9910094.5810097.80
  130.54  130.67  130.67  130.76  130.91  130.87  131.28  131.28  132.61  132.61
  132.79  137.48  137.75  138.41  139.00  139.24  139.45
 -869.46 -869.33 -869.33 -869.24 -869.09 -869.13 -868.72  125.28  126.61 -867.39
 -867.21 -862.52 -862.25 -861.59 -861.00 -860.76 -860.55
BR Coef=-1 , 0 , 0 ,, 0 ,,,0.8,0,1,0,
WSPro=,,,, 1 ,,,, 0 ,,,, 0 ,,,,-1 ,-1 ,-1 , 0 , 0 , 0 , 0 , 0
BC Design=,, 0 ,, 0 ,,,,,,

Type RM Length L Ch R = 1 ,17704.06,129.001200,129.001200,129.001200
XS GIS Cut Line= 2
864529.992282202752540.200867355864811.262499937752093.192014998
#Sta/Elev= 30
9799.582127.54789829.357129.41179900.246129.56689923.876129.19899935.691126.5434
9947.506121.75639959.321116.55379971.136108.75219994.76697.543299996.75497.17301
10006.5899.85545 10018.4105.752210034.31109.421110042.03112.691810065.66128.0121
10071.86131.641210090.64140.6785 10101.1141.211610109.42138.293710112.92138.7611
10124.73143.588310160.17143.661710207.43144.733110219.25145.377110231.06148.9137
10240.85 150.42110278.32150.631610290.14153.267410315.96153.364610327.72154.4565
#Mann= 3 , 0 , 0
9799.582    0.04       09799.582    0.04       010327.72    0.04       0
#XS Ineff= 2 , 0
       0                               0
Bank Sta=9799.582,10327.72
Exp/Cntr=0.3,0.1