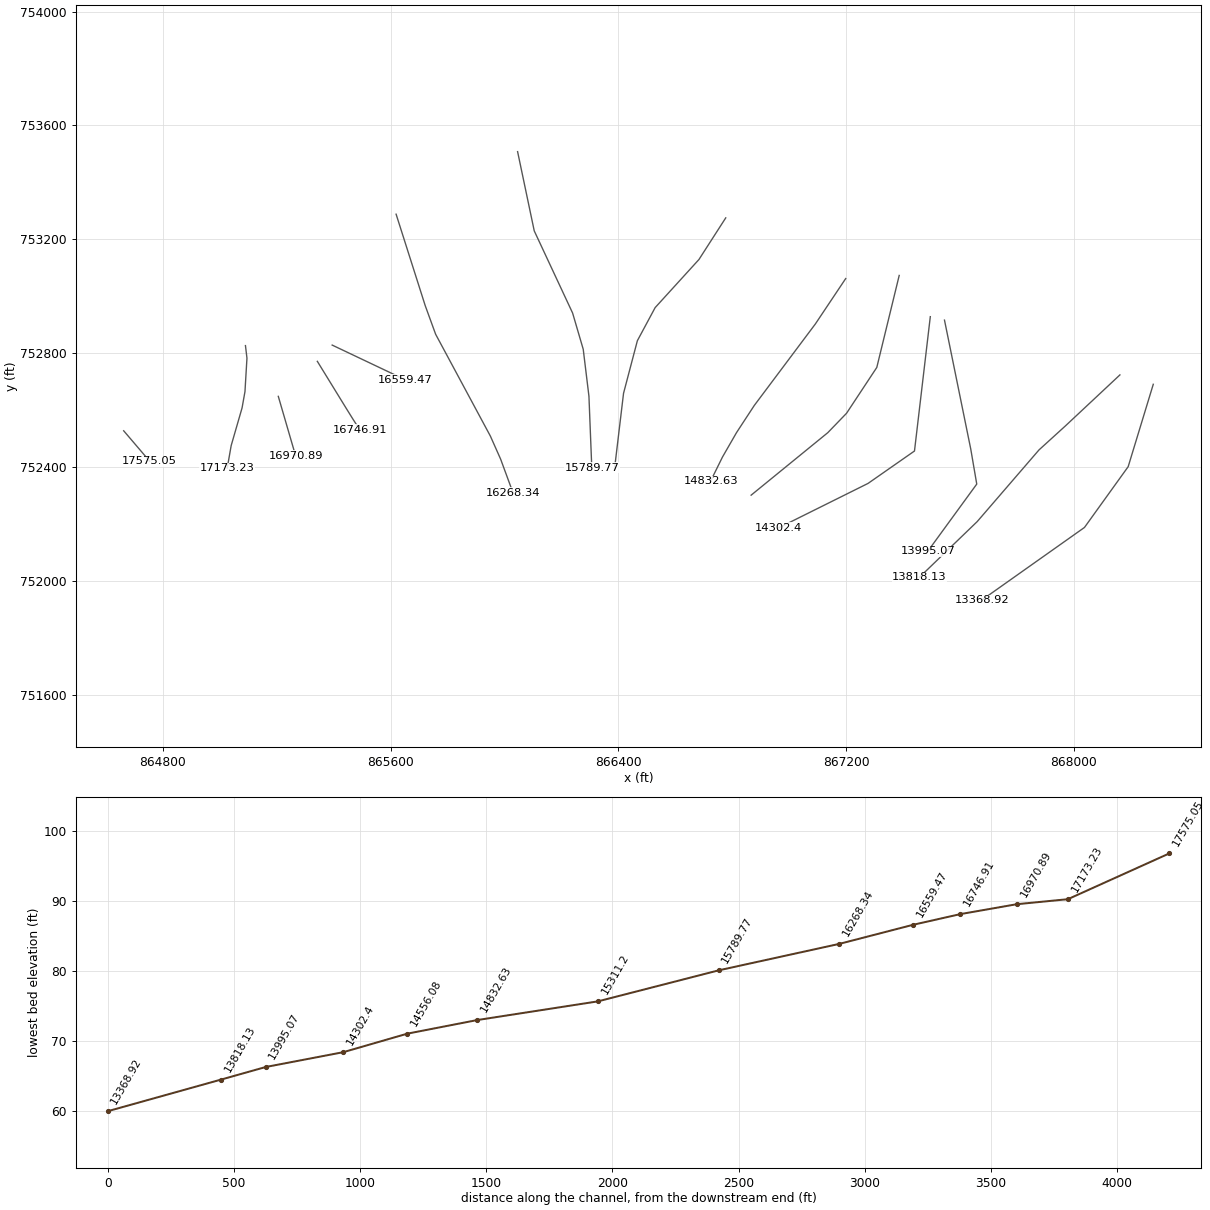
HEC-RAS study 9102_ras.prj: 9102

--- 9102_ras.g01 (geometry) --- (continued)

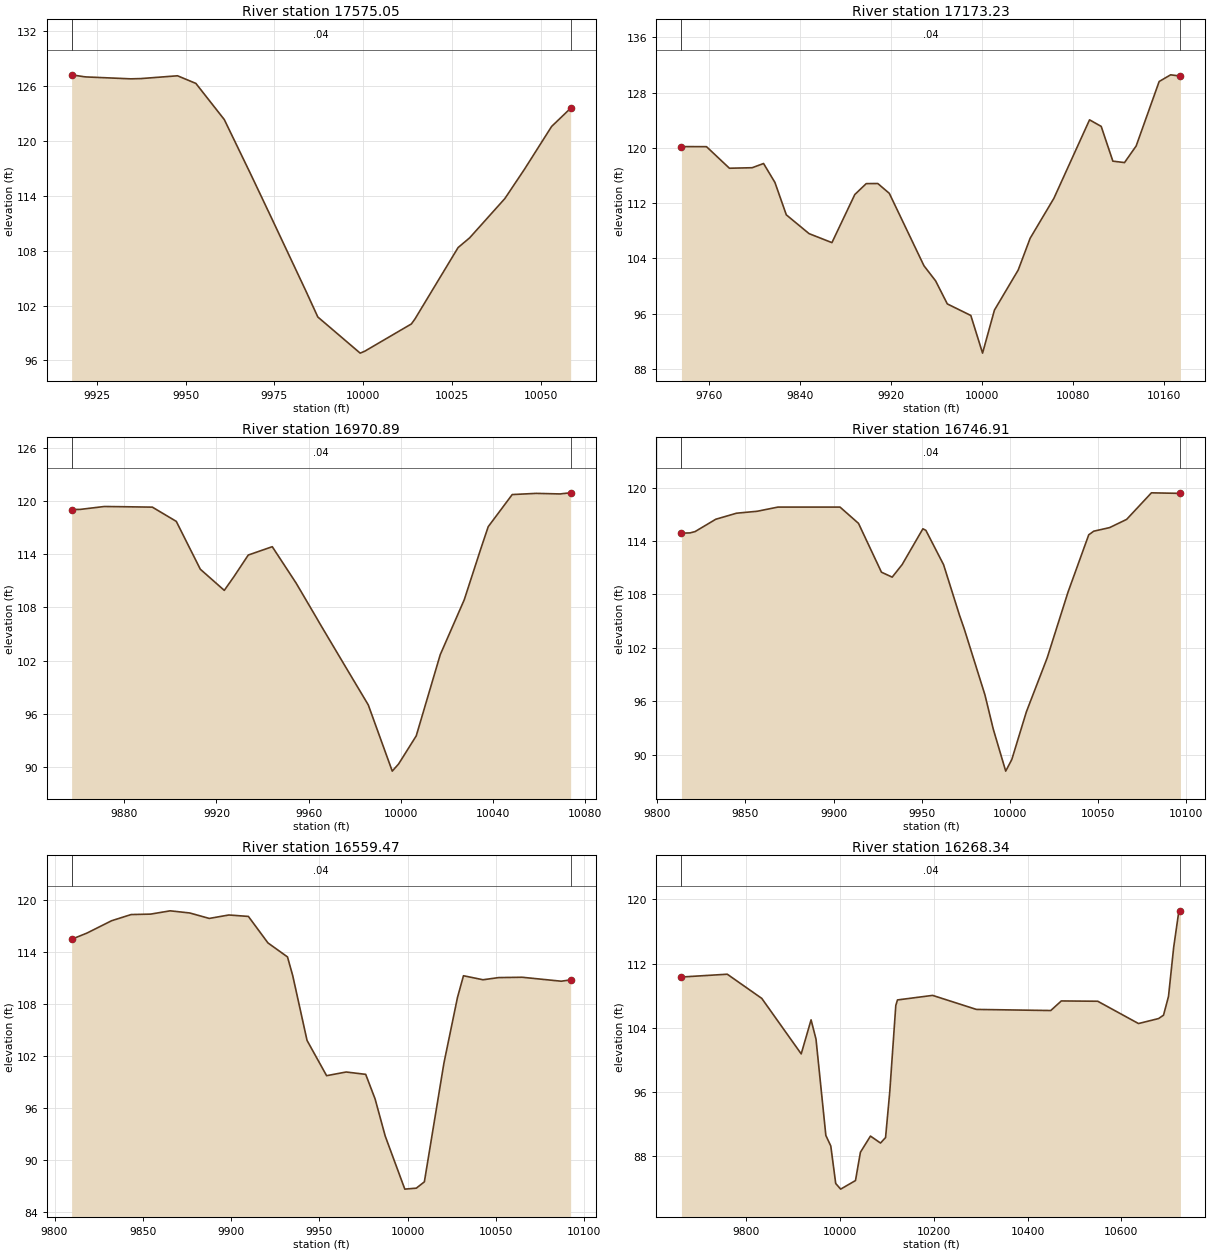
Type RM Length L Ch R = 1 ,17575.05,401.827200,401.827200,401.827200
XS GIS Cut Line= 2
864662.302044763752527.652419805864753.443837484  752420.9321412
#Sta/Elev= 22
9917.971127.21569921.459127.00849922.125126.98479934.609126.77629937.523126.8064
 9947.76127.11119952.922126.2757 9960.91 122.325 9968.32116.37439974.061111.6767
9983.718103.70879987.211100.74989999.11696.8013810000.3696.9990410013.5199.98849
10014.51100.522210026.66108.338910029.91109.400610039.81113.693810045.31116.8871
10052.96121.573210058.31123.5664
#Mann= 3 , 0 , 0
9917.971    0.04       09917.971    0.04       010058.31    0.04       0
#XS Ineff= 2 , 0
       0                               0
Bank Sta=9917.971,10058.31
Exp/Cntr=0.3,0.1

Type RM Length L Ch R = 1 ,17173.23,202.336800,202.336800,202.336800
XS GIS Cut Line= 6
865089.960465284752826.882070139865095.221713866752783.052946793
865088.244307479752665.212472963865078.065138343752608.089303962
865039.864131763752475.946905573865025.831972179752396.379653155
#Sta/Elev= 30
9735.401120.1815 9757.44120.16719777.583117.04459797.605117.1187 9807.61117.7298
9817.614114.98559827.619110.29279847.631107.57039867.727106.26739887.824 113.233
9897.875114.81539908.032114.8325 9918.19113.40519948.662102.91429958.872100.7349
9969.19897.389259989.849 95.717210000.1890.2623810010.6196.4914610031.54102.3097
   10042 106.89510062.92112.695510094.24124.055710104.49123.105810114.74118.0719
10124.99 117.86310135.24120.275210155.45129.607610165.51130.575110174.18130.3945
#Mann= 3 , 0 , 0
9735.401    0.04       09735.401    0.04       010174.18    0.04       0
#XS Ineff= 2 , 0
       0                               0
Bank Sta=9735.401,10174.18
Exp/Cntr=0.3,0.1

Type RM Length L Ch R = 1 ,16970.89,223.976400,223.976400,223.976400
XS GIS Cut Line= 2
865205.342434069752648.623231408865265.866192307752440.649837561
#Sta/Elev= 29
9857.143119.02879860.916119.04669871.331119.37369881.746  119.349891.705119.3025
9892.161119.30489902.576117.69579912.991112.30719923.405109.91969927.493111.4275
 9933.82113.90249944.235114.8414 9954.65110.71369963.281106.89579965.065106.0966
 9975.48 101.5479985.89597.017229996.30989.547069999.06890.3528510006.7293.51907
10017.14 102.67210027.55108.854810034.86114.698810037.97 117.10110048.38120.7188
 10058.8120.852210069.21120.788310070.64120.836710073.74120.9143
#Mann= 3 , 0 , 0
9857.143    0.04       09857.143    0.04       010073.74    0.04       0
#XS Ineff= 2 , 0
       0                               0
Bank Sta=9857.143,10073.74
Exp/Cntr=0.3,0.1

Type RM Length L Ch R = 1 ,16746.91,187.446100,187.446100,187.446100
XS GIS Cut Line= 5
865342.441823354752771.595728357 865439.45501431752613.762760594
865440.484005832752612.047774654865465.482780598752571.819887346
 865491.37382771 752531.11376013
#Sta/Elev= 30
9813.736114.88719818.621114.91339821.478115.06339833.216116.44939844.954117.1272
9856.692117.3466 9868.43117.81549903.644117.81419914.105115.9861 9927.12110.4964
9933.202109.94089938.858111.35639950.596115.37389952.299 115.2029962.334111.3375
9971.396 105.6359974.072104.1052 9985.8196.683149990.492 92.85969997.54888.13057
   1000189.43436 10009.394.8161710021.07100.868910032.84108.237410044.62114.6992
10047.45115.105610056.45115.5096 10066.1116.432810080.15119.419210096.61119.3563
#Mann= 3 , 0 , 0
9813.736    0.04       09813.736    0.04       010096.61    0.04       0
#XS Ineff= 2 , 0
       0                               0
Bank Sta=9813.736,10096.61
Exp/Cntr=0.3,0.1

Type RM Length L Ch R = 1 ,16559.47,291.124700,291.124700,291.124700
XS GIS Cut Line= 2
865394.586829219752828.704023359865649.820767772752707.512657692
#Sta/Elev= 30
9809.688115.51289818.324116.22169832.286117.65179843.356118.36889854.426118.4214
9865.496 118.8019876.566118.55229887.636 117.9219898.706118.31869909.776 118.154
9920.846115.08839931.916113.46769934.894111.28889942.986103.80629954.05699.72639
9965.126100.15289976.196 99.88079981.522 97.03029987.26692.726479998.33686.60148
10004.8486.7122210009.4187.4438810020.48101.174710028.15108.766410031.55111.2898
10042.62110.825610051.46111.075910064.76111.1143 10086.9110.657610092.23110.8142
#Mann= 3 , 0 , 0
9809.688    0.04       09809.688    0.04       010092.23    0.04       0
#XS Ineff= 2 , 0
       0                               0
Bank Sta=9809.688,10092.23
Exp/Cntr=0.3,0.1

Type RM Length L Ch R = 1 ,16268.34,478.570900,478.570900,478.570900
XS GIS Cut Line= 6
 865619.08815645753288.466728603865721.359919365752967.235777009
865757.992205873752866.629394982865950.220494912752509.034131632
865986.198159055752428.158269568866029.392174147752310.731740979
#Sta/Elev= 30
9661.871110.32749759.625110.67839833.193107.66289917.271100.74479938.291104.9887
9948.801102.5859 9969.8290.57428 9980.3389.26546 9990.8484.5872910001.3783.88601
10032.9884.9527210043.5188.4856910064.9390.4974410086.3989.6290710097.1290.31466
 10106.196.0366810118.96106.788810122.54107.471510197.45108.038510290.82106.2887
 10449.4106.150310471.86107.345410549.49107.308110636.43104.528810679.13105.1477
10689.77105.5678 10700.4107.901910711.44114.023410721.44 118.11910725.92118.5802
#Mann= 3 , 0 , 0
9661.871    0.04       09661.871    0.04       010725.92    0.04       0
#XS Ineff= 2 , 0
       0                               0
Bank Sta=9661.871,10725.92
Exp/Cntr=0.3,0.1

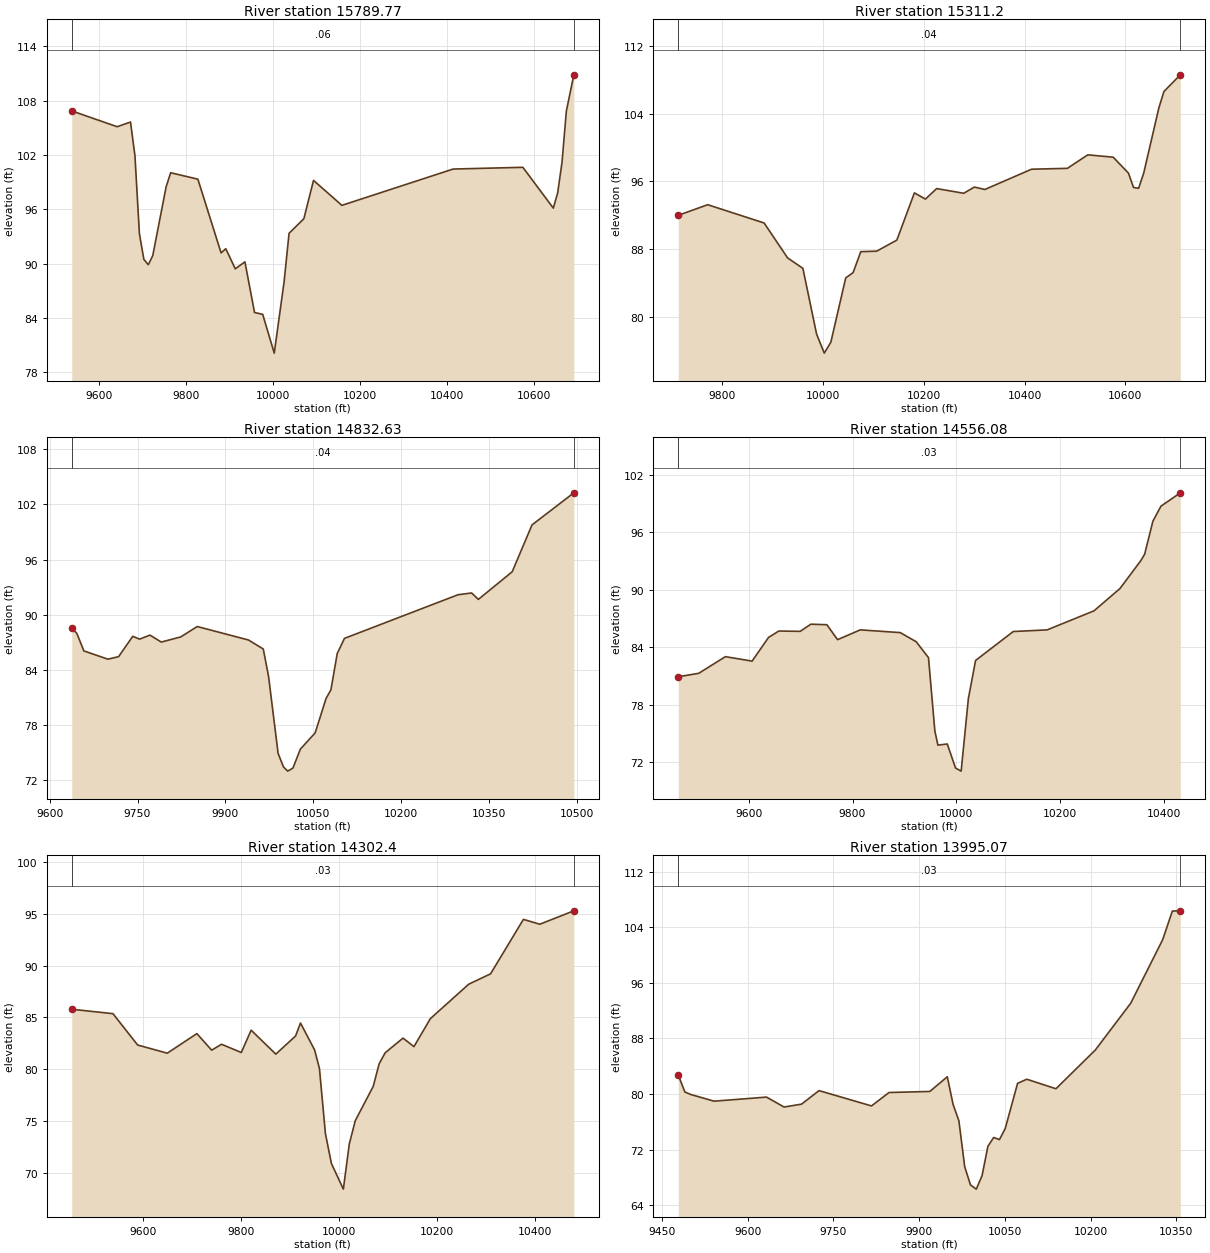
Type RM Length L Ch R = 1 ,15789.77,478.570800,478.570800,478.570800
XS GIS Cut Line= 6
866045.808048322753508.174845248866104.271811032753229.879222304
866239.040420324752941.237625574866276.336918264752814.055157256
866296.417310765752648.926429271866306.392770094752397.845202075
#Sta/Elev= 30
9537.153106.87069641.533105.12359672.198105.64079682.426101.89869692.65593.29294
9702.88390.464419713.11189.871749723.33990.882089754.13898.497629764.543100.0372
9827.07399.323749880.39291.175519891.19291.64172    991389.41874 9935.1790.18736
 9957.3484.586919976.06284.3864810002.6280.1005910025.2987.9985410036.6393.34244
10070.6494.9518110092.88 99.193110158.07 96.433310413.82100.445310574.08100.6373
10644.1296.1267110654.1297.8109210664.13101.212410674.13 106.86810691.29110.8591
#Mann= 3 , 0 , 0
9537.153    0.06       09537.153    0.06       010691.29    0.06       0
#XS Ineff= 2 , 0
       0                               0
Bank Sta=9537.153,10691.29
Exp/Cntr=0.3,0.1

Type RM Length L Ch R = 1 , 15311.2,478.570800,478.570800,478.570800
XS GIS Cut Line= 6
 866776.87895731753275.537758346 866682.76429837753129.272997429
866528.880884972752960.258136936866466.516555096752844.091191707
866417.945278765 752659.41090378866386.085776777752392.647539925
#Sta/Elev= 30
9713.69791.989669772.081 93.24879883.92891.083029930.48486.945659960.71285.71743
9987.848 77.939310003.0975.6702510016.1776.9650110045.6184.5730210060.3285.20915
10075.4787.6859310106.9587.7447310146.9689.0546210181.7694.6464910203.65 93.9134
10225.8595.1574210279.5394.6032310300.6795.3372810321.3895.0500510413.8697.45063
10485.0197.5560710525.3299.1526210575.7198.8759110605.9596.9906810616.0395.28771
 10626.195.1907410636.1896.9792710666.28104.719210676.31106.657310708.76  108.63
#Mann= 3 , 0 , 0
9713.697    0.04       09713.697    0.04       010708.76    0.04       0
#XS Ineff= 2 , 0
       0                               0
Bank Sta=9713.697,10708.76
Exp/Cntr=0.3,0.1

Type RM Length L Ch R = 1 ,14832.63,276.549000,276.549000,276.549000
XS GIS Cut Line= 6
867198.223002172753062.342542789867091.579624936752902.767162584
866877.206370043752616.729811507866814.968200415752521.606487615
866765.469973417752435.573782943866723.763952259752350.973429152
#Sta/Elev= 30
9637.75288.564379646.46887.968669658.33886.068769699.41385.16665 9717.6985.44526
9741.81187.652059753.52587.346099771.07287.787079790.48987.028139823.71387.58912
9851.83788.717599939.19987.254529964.53586.275779973.62683.261469989.87174.91943
    999973.45541 10006.272.9984910015.1973.3322710027.8275.3869810053.0877.15913
10071.6780.8953610079.9781.8389510090.7185.7765110103.0487.4283310296.8392.17383
10320.0492.3629410331.5891.6699810389.2694.6687510423.1499.7678810494.47103.2522
#Mann= 3 , 0 , 0
9637.752    0.04       09637.752    0.04       010494.47    0.04       0
#XS Ineff= 2 , 0
       0                               0
Bank Sta=9637.752,10494.47
Exp/Cntr=0.3,0.1

Type RM Length L Ch R = 1 ,14556.08,253.681400,253.681400,253.681400
XS GIS Cut Line= 6
867386.176591122753073.342329014867307.450440147752750.156415653
867201.039495172752588.957893142867199.608742405752587.560419806
867135.318402338752521.053163825866866.100246555752301.586114913
#Sta/Elev= 30
9464.14180.909729503.60481.270419555.06683.010179606.52882.545759638.12185.01541
 9657.9985.68683 9699.1685.653679719.74586.400849750.62286.345889771.20784.78627
9814.93885.806959891.98385.523699922.77984.569229946.43882.909549958.726 75.2452
 9964.5973.772789982.69173.890829998.56171.38236 10009.4 71.056710023.3178.63028
10037.2282.6136610109.84 85.635310175.1585.8076210265.4787.7951110315.58 90.1317
10355.7893.0459110363.0693.7125310378.8997.1487410394.4898.7256410431.77100.1196
#Mann= 3 , 0 , 0
9464.141    0.03       09464.141    0.03       010431.77    0.03       0
#XS Ineff= 2 , 0
       0                               0
Bank Sta=9464.141,10431.77
Exp/Cntr=0.3,0.1

Type RM Length L Ch R = 1 , 14302.4,307.334400,307.334400,307.334400
XS GIS Cut Line= 4
 867495.40555302752928.531635446867439.838154588752456.654647685
 867276.79045648 752342.89990588866962.837355906752186.805170994
#Sta/Elev= 30
 9454.7685.793149538.86885.364979589.21482.337299649.62981.548739710.04383.43785
 9740.2581.841879760.38982.408919800.66581.615389820.80383.771449871.14981.45466
9911.42583.206529921.49484.463159950.26681.867089960.18380.069029972.37673.78237
9984.56970.8957310008.9668.4125410021.1572.7919110033.3475.0310810069.9278.33776
10082.1280.5344810094.3181.58695 10130.783.0038910153.0482.1806910186.5484.88473
10264.7288.2107610309.3989.21414 10376.494.47485 10409.994.0090310479.3295.30316
#Mann= 3 , 0 , 0
 9454.76    0.03       0 9454.76    0.03       010479.32    0.03       0
#XS Ineff= 2 , 0
       0                               0
Bank Sta=9454.76,10479.32
Exp/Cntr=0.3,0.1

Type RM Length L Ch R = 1 ,13995.07,176.935900,176.935900,176.935900
XS GIS Cut Line= 4
867545.196636341752916.418784987867637.494150068 752463.46453755
867658.537700629 752340.47665313867486.815820039752104.864583664
#Sta/Elev= 30
9478.47882.716529490.131 80.27899500.33779.922899541.15978.958199633.00879.54486
9663.62478.116039694.241 78.52919724.85780.478869816.70778.273069847.323 80.2052
9918.76280.358179949.32782.469499959.47378.482659969.61876.138329979.76369.52541
9989.90966.9020410000.0566.29495 10010.268.2427510020.3472.4557910030.4973.73081
10040.6473.4249710050.7875.0461610072.2981.52519 10088.5 82.116110139.4380.74827
10208.4186.3298810270.28 93.059810326.19102.203910343.17106.330710357.07106.3636
#Mann= 3 , 0 , 0
9478.478    0.03       09478.478    0.03       010357.07    0.03       0
#XS Ineff= 2 , 0
       0                               0
Bank Sta=9478.478,10357.07
Exp/Cntr=0.3,0.1

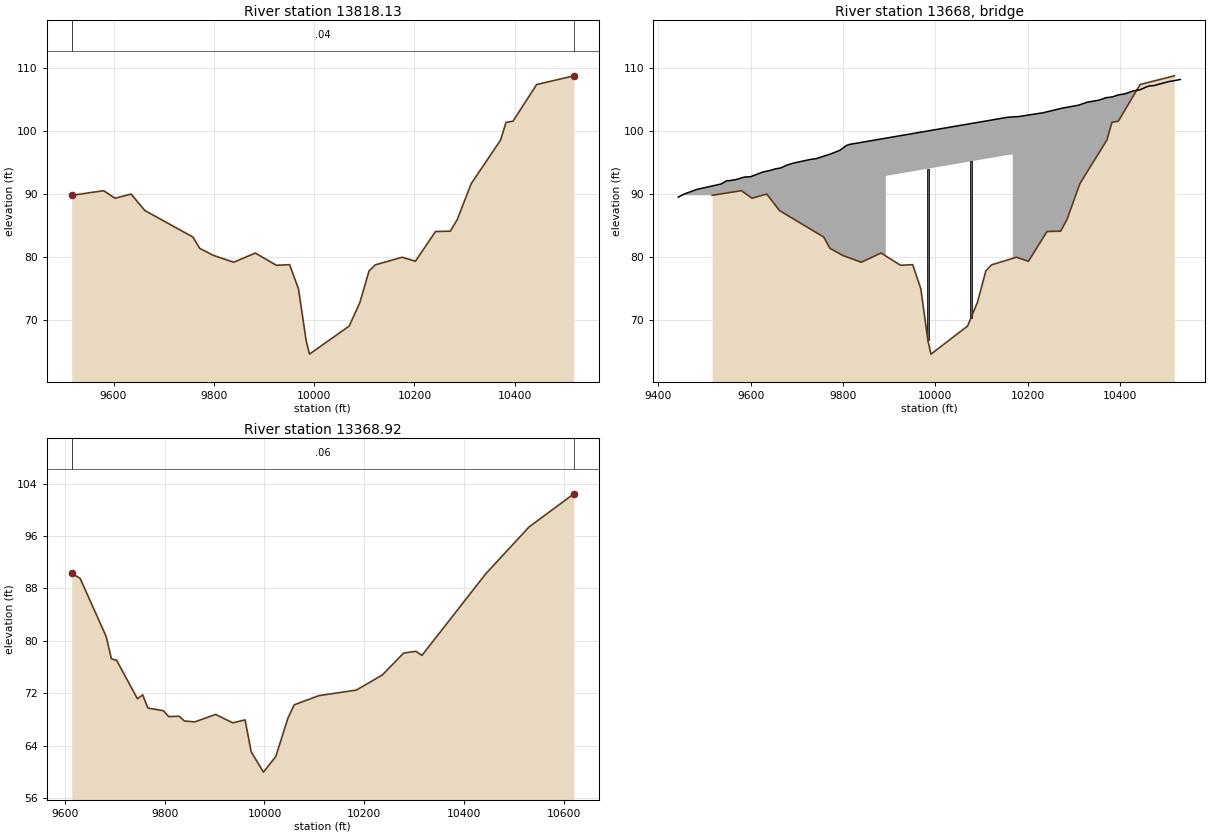
Type RM Length L Ch R = 1 ,13818.13,449.211900,449.211900,449.211900
XS GIS Cut Line= 5
868161.376423312 752723.98240668867970.414273776752545.259480462
867877.099687165752460.404169792867660.036550571752208.643557667
867457.640412656752013.538429847
#Sta/Elev= 30
9516.66489.740319580.18390.471739602.981 89.26999634.96989.935839662.36287.32267
9758.23783.109339771.93381.308589799.04980.193629839.59879.101099882.64680.56448
 9924.6878.620969951.08878.717959968.814 74.85819984.12866.617749990.69864.49818
10069.9268.9584210091.3372.7306910109.5377.7349510121.9678.6863310175.5579.89391
10201.9679.2604710242.0183.9869210271.5384.0374110285.4285.89489 10313.291.58425
10371.6998.5056810382.65101.326610396.54 101.52210443.73 107.34510517.88108.7269
#Mann= 3 , 0 , 0
9516.664    0.04       09516.664    0.04       010517.88    0.04       0
#XS Ineff= 2 , 0
       0                               0
Bank Sta=9516.664,10517.88
Exp/Cntr=0.3,0.1

Type RM Length L Ch R = 3 ,   13668,,,
BEGIN DESCRIPTION:
END DESCRIPTION:
Bridge Culvert--1,0,-1,-1, 0
Deck Dist Width WeirC Skew NumUp NumDn MinLoCord MaxHiCord MaxSubmerge Is_Ogee
164.605950,120.000000,2.6,0, 45, 44, , , 0.95, 0, 0,0,,
 9443.19 9457.51 9484.15 9535.78 9548.69 9552.39 9568.20 9587.42 9599.83 9626.14
 9647.27 9651.96 9664.87 9677.78 9690.69 9729.41 9742.15 9773.78 9789.59 9793.96
 9806.87 9813.58 9892.87 9892.8710155.8510165.7510167.8710167.8710179.3310233.66
10274.4110310.2810328.7410354.6110369.3910384.1710396.6610410.2410428.5010443.28
10458.0510464.5710472.8310505.3210530.81
   89.45   89.98   90.69   91.53   92.07   92.05   92.24   92.65   92.69   93.43
   93.78   93.92   94.08   94.51   94.82   95.44   95.57   96.32   96.78   96.93
   97.63   97.82   98.82   98.82  102.13  102.20  102.20  102.20  102.24  102.86
  103.58  104.06  104.53  104.86  105.24  105.39  105.70  105.85  106.33  106.50
  106.99  107.13  107.16  107.80  108.14
 -910.55 -910.02 -909.31 -908.47 -907.93 -907.95 -907.76 -907.35 -907.31 -906.57
 -906.22 -906.08 -905.92 -905.49 -905.18 -904.56 -904.43 -903.68 -903.22 -903.07
 -902.37 -902.18 -901.18   92.82   96.13   96.20   96.20 -897.80 -897.76 -897.14
 -896.42 -895.94 -895.47 -895.14 -894.76 -894.61 -894.30 -894.15 -893.67 -893.50
 -893.01 -892.87 -892.84 -892.20 -891.86
 9443.19 9457.51 9484.15 9535.78 9548.69 9552.39 9568.20 9587.42 9599.83 9626.14
 9647.27 9651.96 9664.87 9677.78 9690.69 9729.41 9742.15 9773.78 9789.59 9793.96
 9806.87 9813.58 9867.85 9867.8510142.8510142.8510162.5210179.3310233.6610274.41
10310.2810328.7410354.6110369.3910384.1710396.6610410.2410428.5010443.2810458.05
10464.5710472.8310505.3210530.81
   89.45   89.98   90.69   91.53   92.07   92.05   92.24   92.65   92.69   93.43
   93.78   93.92   94.08   94.51   94.82   95.44   95.57   96.32   96.78   96.93
   97.63   97.82   98.50   98.50  101.96  101.96  102.19  102.24  102.86  103.58
  104.06  104.53  104.86  105.24  105.39  105.70  105.85  106.33  106.50  106.99
  107.13  107.16  107.80  108.14
 -910.55 -910.02 -909.31 -908.47 -907.93 -907.95 -907.76 -907.35 -907.31 -906.57
 -906.22 -906.08 -905.92 -905.49 -905.18 -904.56 -904.43 -903.68 -903.22 -903.07
 -902.37 -902.18 -901.50   92.50   95.96 -898.04 -897.81 -897.76 -897.14 -896.42
 -895.94 -895.47 -895.14 -894.76 -894.61 -894.30 -894.15 -893.67 -893.50 -893.01
 -892.87 -892.84 -892.20 -891.86
Pier Skew, UpSta & Num, DnSta & Num=  ,9983.87, 2 ,9958.85, 2 , 0 , 0 , 0 ,,
    4.00    4.00
 -900.04   99.96
    4.00    4.00
 -900.35   99.65
Pier Skew, UpSta & Num, DnSta & Num=  ,10076.87, 2 ,10051.85, 2 , 0 , 0 , 0 ,,
    4.00    4.00
 -898.87  101.13
    4.00    4.00
 -899.18  100.82
BR Coef=-1 , 0 , 0 ,, 0 ,,,0.8,0,1,0,
WSPro=,,,, 1 ,,,, 0 ,,,, 0 ,,,,-1 ,-1 ,-1 , 0 , 0 , 0 , 0 , 0
BC Design=,, 0 ,, 0 ,,,,,,

Type RM Length L Ch R = 1 ,13368.92,398.710500,398.710500,398.710500
XS GIS Cut Line= 4
868278.557870121752691.084193846868190.382278725752401.604775626
 868036.89250808752188.157752618867676.242366717751933.091378332
#Sta/Elev= 30
9613.41990.294819630.23389.532359682.50180.664749692.954  77.2679703.40877.03365
9745.22371.169419755.67671.76612 9766.1369.760849797.49169.343699807.94468.44509
9828.85268.508299839.305 67.78119860.212 67.64329902.027 68.78269936.48267.49429
9961.11667.948379973.43363.061119998.06759.97903 10022.762.3666610047.3468.26657
10059.6570.2458710108.9271.64098 10184.472.4981910236.3674.7943610279.24 78.1399
10303.7378.4091110315.9877.7887910444.1890.2545110530.7797.3733310620.67102.4304
#Mann= 3 , 0 , 0
9613.419    0.06       09613.419    0.06       010620.67    0.06       0
#XS Ineff= 2 , 0
       0                               0
Bank Sta=9613.419,10620.67
Exp/Cntr=0.3,0.1