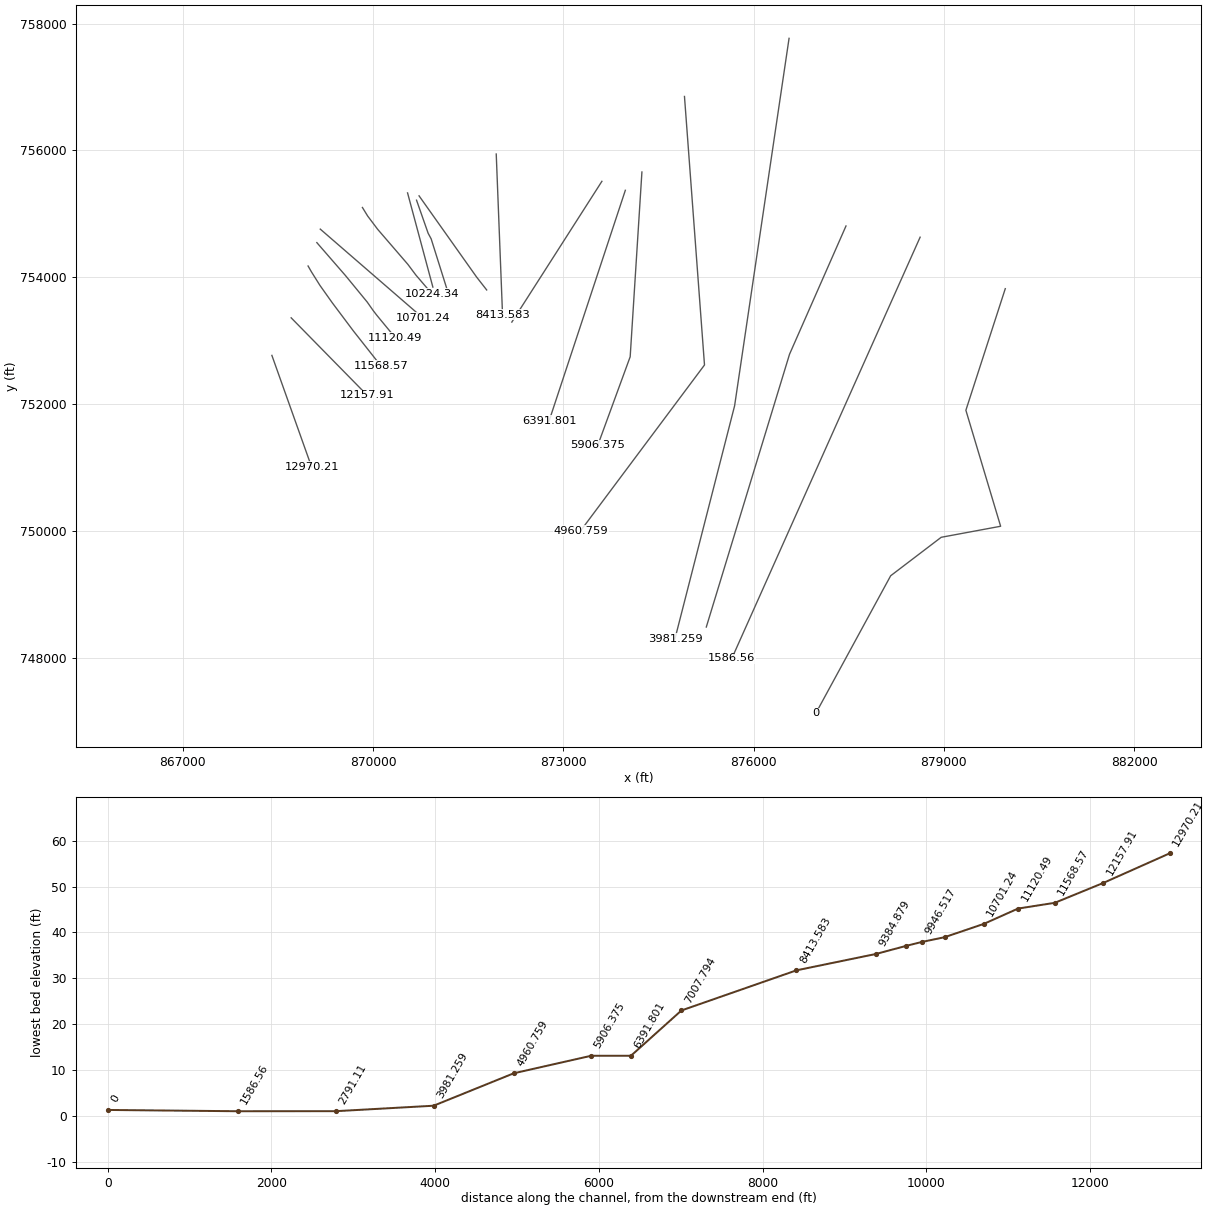
HEC-RAS study 9102_ras.prj: 9102

--- 9102_ras.g01 (geometry) --- (continued)

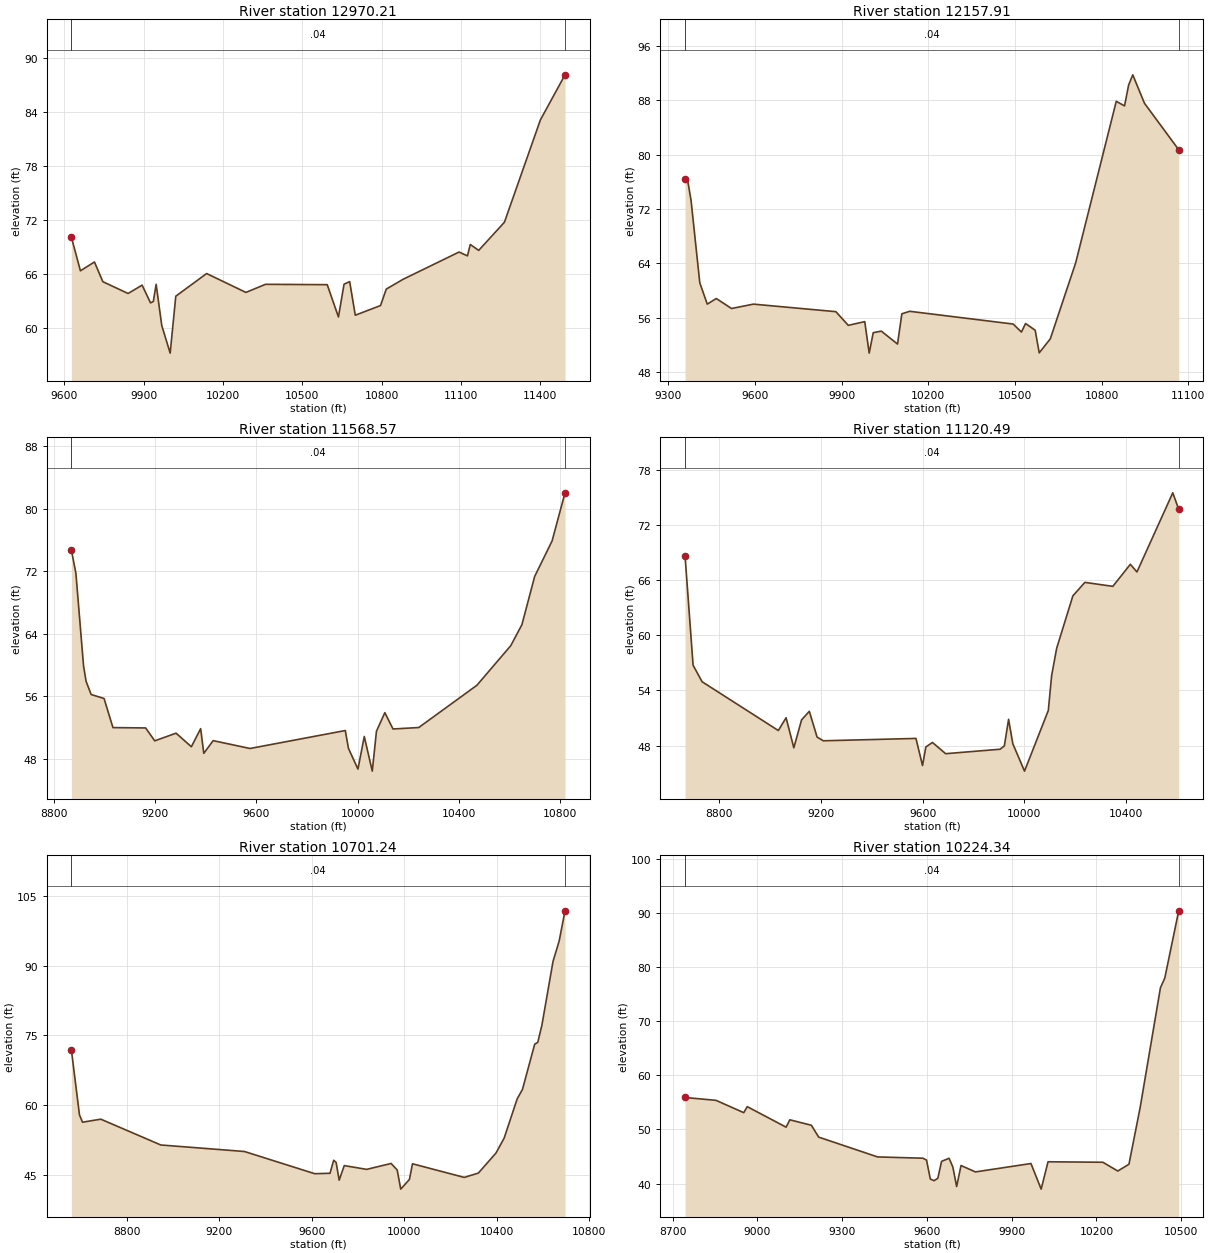
Type RM Length L Ch R = 1 ,12970.21,812.295300,812.295300,812.295300
XS GIS Cut Line= 2
868405.316383485752767.335629005869031.891341417751007.226986095
#Sta/Elev= 30
9626.15170.127039660.47566.372519713.54867.354879745.392 65.16469840.92563.85632
9893.99964.782999925.84362.811939936.45862.966769947.07264.876039968.30260.30704
10000.1557.2347410021.3863.5533810138.1466.0712510286.7463.9749110361.0564.87375
10594.5764.8338210637.0361.2476210658.2664.8919310679.4965.1733510700.7261.44356
10796.2562.5170810817.9264.3395510881.1765.4240511093.4668.4573411125.3168.03367
11135.9269.2954511167.7768.6402511265.1971.7670311401.29 83.124311494.4688.13204
#Mann= 3 , 0 , 0
9626.151    0.04       09626.151    0.04       011494.46    0.04       0
#XS Ineff= 2 , 0
       0                10077.76       0
Bank Sta=9626.151,11494.46
Exp/Cntr=0.3,0.1

Type RM Length L Ch R = 1 ,12157.91,589.342000,589.342000,589.342000
XS GIS Cut Line= 2
868709.220544732753359.842805506869906.397494309752140.474591898
#Sta/Elev= 30
  9358.476.43997 9366.6576.416959379.20173.264619409.47161.126549435.25757.99197
9466.56658.813479519.341 57.34519595.03157.988779880.50756.878329923.32854.86598
9980.42355.411039995.819 50.770810009.8353.7839610037.8654.0110110093.9252.10789
10108.8956.5649710135.9656.9334110494.2855.0551510522.8353.87519 10537.155.13212
10570.39 54.147310584.4150.8143710622.7452.8727910710.53 64.067410851.1387.87286
10879.6787.1937510893.9590.2814810908.2291.7738510948.7787.5780111067.2380.73705
#Mann= 3 , 0 , 0
  9358.4    0.04       0  9358.4    0.04       011067.23    0.04       0
#XS Ineff= 2 , 0
       0                10206.23       0
Bank Sta=9358.4,11067.23
Exp/Cntr=0.3,0.1

Type RM Length L Ch R = 1 ,11568.57,448.078500,448.078500,448.078500
XS GIS Cut Line= 6
  868976.0429749754176.860339677869027.213342182754087.602812009
869163.239836223 753870.93250283869357.950370188753596.341943444
869690.237314123753153.148575279870126.233925045752600.045473993
#Sta/Elev= 30
8867.30374.712398885.31271.742258915.55459.910768925.52557.944878945.63156.24896
8996.73855.739069031.97752.021569161.40851.978229197.26950.32916 9281.71  51.311
9342.31149.575729379.02851.887049391.38348.733959428.44650.35609 9574.46 49.3545
9951.43151.648019963.91749.3702110001.4746.7249710026.5450.8842510058.1946.46349
10074.7751.5627210107.9453.9275710140.3151.84487 10242.152.0317310472.2357.42608
10606.3762.4908110650.3365.1660710700.8971.3298210769.8675.8665610820.92 82.0046
#Mann= 3 , 0 , 0
8867.303    0.04       08867.303    0.04       010820.92    0.04       0
#XS Ineff= 2 , 0
       09748.648        10069.31       0
Bank Sta=8867.303,10820.92
Exp/Cntr=0.3,0.1

Type RM Length L Ch R = 1 ,11120.49,419.253600,419.253600,419.253600
XS GIS Cut Line= 6
 869114.22744817754545.614407901869567.352812578754024.287951133
869908.385108941753608.552376611870004.070058512753472.424731179
870059.967803787753399.828695361870349.829178979753048.197529796
#Sta/Elev= 30
8665.42468.662698697.08956.748338732.48554.953189032.44949.636879062.93651.02773
9093.42347.75234 9123.9150.800669154.39851.727119184.88548.923119209.46448.51825
9573.81548.77422 9599.7945.823819612.778 47.84239638.75448.336119690.704 47.1119
9904.93847.597949921.63547.958589938.33250.855869955.07248.18686   1000145.21197
10094.6351.8230710107.5655.5955810127.4258.59209 10191.364.3127810238.4765.77911
10348.5265.34771 10417.467.7508710443.32 66.912710584.3475.5376710607.6573.73912
#Mann= 3 , 0 , 0
8665.424    0.04       08665.424    0.04       010607.65    0.04       0
#XS Ineff= 2 , 0
       09545.692        10146.19       0
Bank Sta=8665.424,10607.65
Exp/Cntr=0.3,0.1

Type RM Length L Ch R = 1 ,10701.24,476.903300,476.903300,476.903300
XS GIS Cut Line= 2
869168.392921349754758.460449445 870784.19965752753359.428752075
#Sta/Elev= 30
8558.85471.914568594.04957.840178607.27656.275228686.35756.927338946.06851.37176
9308.33649.96655 9612.5745.187169678.70845.276529694.64748.080179705.16347.62774
 9718.3943.794559740.47846.933099837.43846.118589943.25947.391969969.635  45.987
9984.912 41.865810022.6243.9555610035.8547.32329 10259.944.3880710321.0145.31984
10397.3949.6411610432.6852.8549210489.0661.2951810512.0463.3409410564.9573.08029
10578.1873.46226   1059677.1283310644.3290.9082110670.7795.2637110696.17101.7845
#Mann= 3 , 0 , 0
8558.854    0.04       08558.854    0.04       010696.17    0.04       0
#XS Ineff= 2 , 0
       09445.846        10411.11       0
Bank Sta=8558.854,10696.17
Exp/Cntr=0.3,0.1

Type RM Length L Ch R = 1 ,10224.34,277.818400,277.818400,277.818400
XS GIS Cut Line= 6
869833.050360609755099.508288946869915.391703501754965.272719293
870073.728422988754755.078292329870549.339025399754203.210690047
870676.461642731754033.455492752870927.094515209753741.395756658
#Sta/Elev= 30
8744.14455.913388853.74755.384218951.89753.107988964.25954.219899101.75350.42674
9114.93751.788859191.20750.777169217.019 48.58969425.58644.925289585.33544.69266
9598.64844.34715 9611.9640.850519625.27340.532499638.58540.977589651.89844.11052
9678.52244.679719691.83543.042749705.14739.454169720.68943.33847 9771.7142.15751
 9968.1143.7083810004.2838.9758810028.54 44.031110222.6643.9417710275.3742.32082
 10314.943.5771510354.4354.0286410426.3276.1928510441.6777.9868110490.9690.41477
#Mann= 3 , 0 , 0
8744.144    0.04       08744.144    0.04       010490.96    0.04       0
#XS Ineff= 2 , 0
       09404.397        10211.22       0
Bank Sta=8744.144,10490.96
Exp/Cntr=0.3,0.1

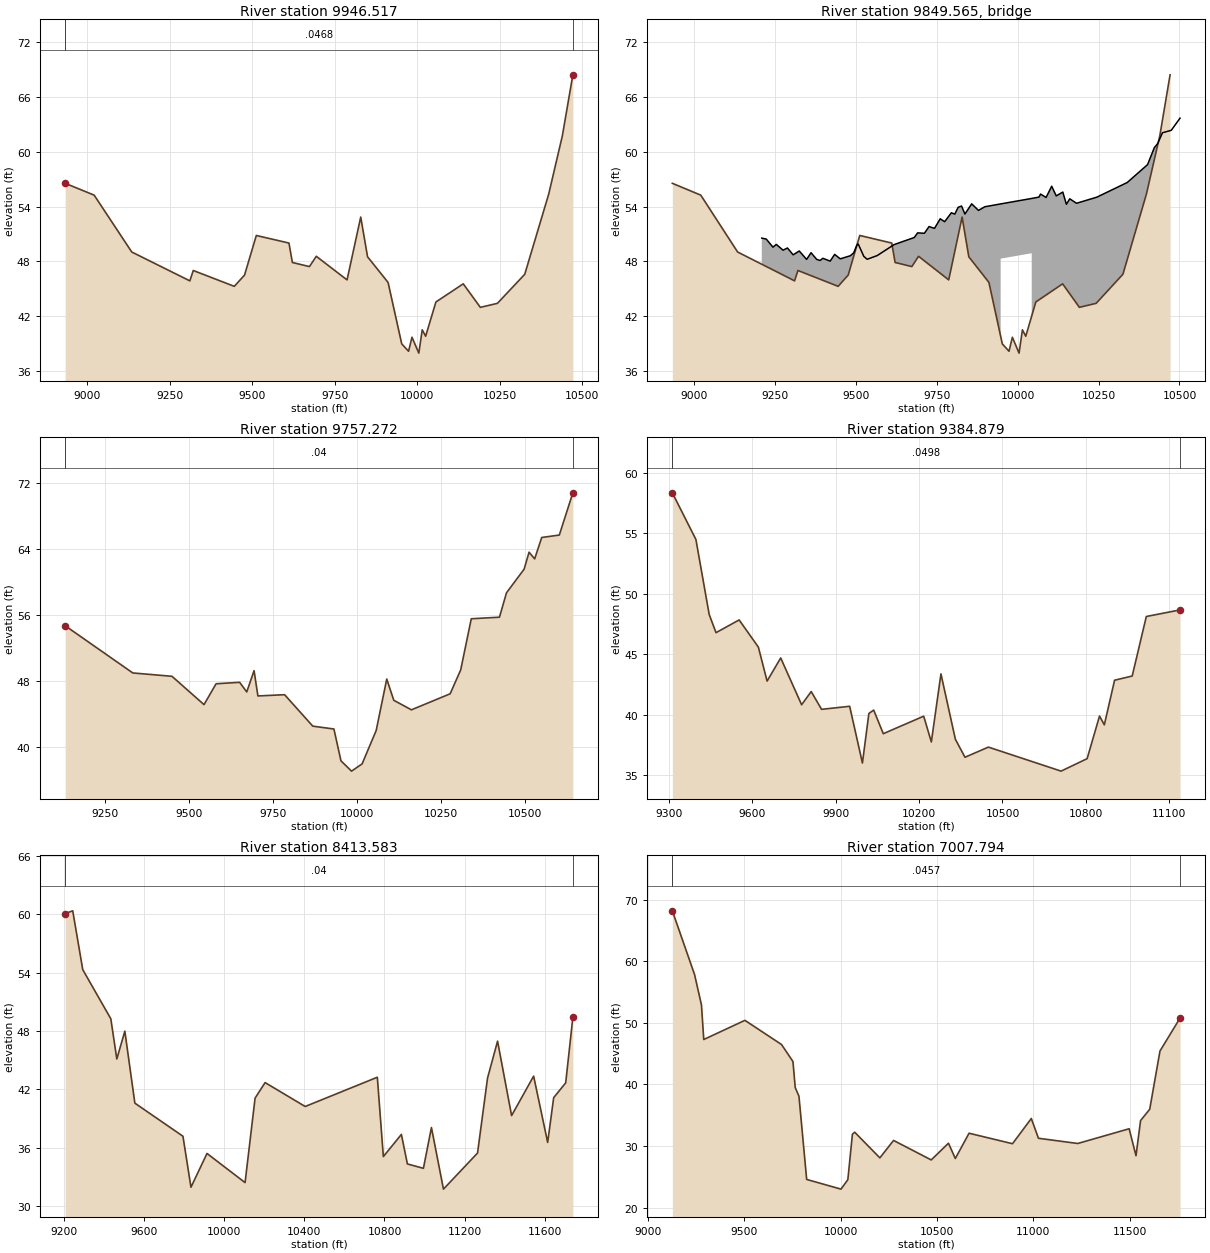
Type RM Length L Ch R = 1 ,9946.517,189.244300,189.244300,189.244300
XS GIS Cut Line= 2
870544.719833427 755329.82423837870943.838958517753844.271809719
#Sta/Elev= 30
8932.79156.549429020.62355.252469134.52449.018969310.55345.855239320.90746.99224
9445.16345.255239476.22746.485529511.98150.830799610.83750.000799621.19147.86981
9672.96447.420259693.67448.548229786.86545.961359828.28452.848239848.993 48.4941
9911.121  45.6869952.53938.944489973.24838.140379983.60339.6749710004.3137.93436
10014.6740.4890410025.0239.7858310056.0943.5410710138.9245.52818 10190.742.95342
10242.4743.3902610325.3146.5798810397.7955.3580910439.2161.7522610471.0268.44064
#Mann= 3 , 0 , 0
8932.791  0.0468       08932.791  0.0468       010471.02  0.0468       0
#XS Ineff= 2 , 0
       09883.623        10045.42       0
Bank Sta=8932.791,10471.02
Exp/Cntr=0.3,0.1

Type RM Length L Ch R = 3 ,9849.565,,,
BEGIN DESCRIPTION:
END DESCRIPTION:
Bridge Culvert--1,0,-1,-1, 0
Deck Dist Width WeirC Skew NumUp NumDn MinLoCord MaxHiCord MaxSubmerge Is_Ogee
51.622150,86.000000,2.6,0, 60, 60, , , 0.95, 0, 0,0,,
 9209.16 9222.91 9243.71 9254.11 9274.90 9288.54 9306.10 9325.01 9347.69 9361.47
 9378.89 9389.29 9397.93 9420.49 9434.40 9451.68 9482.88 9493.28 9503.68 9507.32
 9524.47 9534.87 9566.07 9618.06 9680.45 9690.85 9711.65 9726.10 9742.92 9760.60
 9774.27 9795.06 9805.62 9816.07 9826.52 9836.97 9857.87 9878.77 9898.33 9947.37
 9947.3710043.3710043.3710065.8210070.7410087.7610105.1910119.1210139.4410150.49
10160.9410181.8610244.6010338.7010401.4410422.3510432.8110447.4410474.6410501.75
   50.54   50.44   49.55   49.85   49.22   49.46   48.71   49.13   48.21   48.94
   48.21   48.09   48.33   48.02   48.76   48.27   48.61   48.93   49.83   49.89
   48.54   48.22   48.63   49.83   50.61   51.12   51.07   51.81   51.61   52.66
   52.34   53.32   53.17   53.92   54.06   53.18   54.30   53.58   53.98   54.29
   54.29   54.89   54.89   55.04   55.37   55.00   56.23   55.17   55.59   54.25
   54.85   54.36   55.03   56.64   58.60   60.46   60.91   62.09   62.36   63.69
 -949.46 -949.56 -950.45 -950.15 -950.78 -950.54 -951.29 -950.87 -951.79 -951.06
 -951.79 -951.91 -951.67 -951.98 -951.24 -951.73 -951.39 -951.07 -950.17 -950.11
 -951.46 -951.78 -951.37 -950.17 -949.39 -948.88 -948.93 -948.19 -948.39 -947.34
 -947.66 -946.68 -946.83 -946.08 -945.94 -946.82 -945.70 -946.42 -946.02 -945.71
   48.29   48.89 -945.11 -944.96 -944.63 -945.00 -943.77 -944.83 -944.41 -945.75
 -945.15 -945.64 -944.97 -943.36 -941.40 -939.54 -939.09 -937.91 -937.64 -936.31
 9209.16 9222.91 9243.71 9254.11 9274.90 9288.54 9306.10 9325.01 9347.69 9361.47
 9378.89 9389.29 9397.93 9420.49 9434.40 9451.68 9482.88 9493.28 9503.68 9507.32
 9524.47 9534.87 9566.07 9618.06 9680.45 9690.85 9711.65 9726.10 9742.92 9760.60
 9774.27 9795.06 9805.62 9816.07 9826.52 9836.97 9857.87 9878.77 9898.33 9951.15
 9951.1510047.1510047.1510065.8210070.7410087.7610105.1910119.1210139.4410150.49
10160.9410181.8610244.6010338.7010401.4410422.3510432.8110447.4410474.6410501.75
   50.54   50.44   49.55   49.85   49.22   49.46   48.71   49.13   48.21   48.94
   48.21   48.09   48.33   48.02   48.76   48.27   48.61   48.93   49.83   49.89
   48.54   48.22   48.63   49.83   50.61   51.12   51.07   51.81   51.61   52.66
   52.34   53.32   53.17   53.92   54.06   53.18   54.30   53.58   53.98   54.31
   54.31   54.92   54.92   55.04   55.37   55.00   56.23   55.17   55.59   54.25
   54.85   54.36   55.03   56.64   58.60   60.46   60.91   62.09   62.36   63.69
 -949.46 -949.56 -950.45 -950.15 -950.78 -950.54 -951.29 -950.87 -951.79 -951.06
 -951.79 -951.91 -951.67 -951.98 -951.24 -951.73 -951.39 -951.07 -950.17 -950.11
 -951.46 -951.78 -951.37 -950.17 -949.39 -948.88 -948.93 -948.19 -948.39 -947.34
 -947.66 -946.68 -946.83 -946.08 -945.94 -946.82 -945.70 -946.42 -946.02 -945.69
   48.31   48.92 -945.08 -944.96 -944.63 -945.00 -943.77 -944.83 -944.41 -945.75
 -945.15 -945.64 -944.97 -943.36 -941.40 -939.54 -939.09 -937.91 -937.64 -936.31
BR Coef=-1 , 0 , 0 ,, 0 ,,,0.8,0,1,0,
WSPro=,,,, 1 ,,,, 0 ,,,, 0 ,,,,-1 ,-1 ,-1 , 0 , 0 , 0 , 0 , 0
BC Design=,, 0 ,, 0 ,,,,,,

Type RM Length L Ch R = 1 ,9757.272,372.393000,372.393000,372.393000
XS GIS Cut Line= 4
870686.246895506755214.934881876870869.586522118754692.578280085
870916.555033597754605.725772021871174.103856659753786.598741634
#Sta/Elev= 30
 9130.6854.686819331.97448.972629448.55348.567979543.93645.141879579.84247.66529
9649.91647.840189671.11246.675579692.89349.254879704.26146.191119783.77746.34118
9867.63842.536599930.53442.190999951.49938.343769982.94737.09432 10014.437.96769
10056.3342.0079910087.7748.2345910108.74 45.665510161.1544.5101710276.4646.45103
10307.9149.3436510339.3655.5303810423.2255.7200810444.1858.67126 10496.661.53102
10511.3163.5819910528.0462.7785810549.0165.3637510601.4265.6603410641.6870.76844
#Mann= 3 , 0 , 0
 9130.68    0.04       0 9130.68    0.04       010641.68    0.04       0
#XS Ineff= 2 , 0
       09904.324        10089.92       0
Bank Sta=9130.68,10641.68
Exp/Cntr=0.3,0.1

Type RM Length L Ch R = 1 ,9384.879,971.296400,971.296400,971.296400
XS GIS Cut Line= 3
870725.985079931755283.253693725 871633.25010839754002.872106024
871792.203197693753799.344606919
#Sta/Elev= 30
9311.73858.347979396.51654.489359444.414 48.27749468.92646.776019552.18347.82908
9621.369 45.58159652.76642.76823 9701.7944.681939777.03640.810139811.62941.90182
9848.86240.429829949.999 40.68329995.93535.9877710019.1840.0877810036.4840.36998
10071.07 38.415210216.54  39.86310244.0437.7325810278.6343.3630510330.5237.95419
10365.1136.4651910449.4137.3045410711.04 35.317310804.8336.3494710849.4139.87318
10866.7139.1486410903.6542.8392110967.09 43.188411017.8548.1130611139.2248.65732
#Mann= 3 , 0 , 0
9311.738  0.0498       09311.738  0.0498       011139.22  0.0498       0
#XS Ineff= 2 , 0
       0 9897.02        10279.55       0
Bank Sta=9311.738,11139.22
Exp/Cntr=0.3,0.1

Type RM Length L Ch R = 1 ,8413.583,1405.789300,1405.789300,1405.789300
XS GIS Cut Line= 2
871943.028127795755942.745724348872042.415608028753409.327864873
#Sta/Elev= 30
9205.32260.089639243.09660.366939293.13554.317119433.24349.266239463.26645.12892
9503.29647.990949553.33540.58904 9793.5237.18591 9833.5531.939979913.61235.41392
10103.7632.41866 10153.841.1082910203.8342.7027610403.9940.2442410764.2743.25252
10794.2935.0905610884.3637.3722610914.3834.3366410994.4433.8873811034.4738.08198
11094.5231.7464511264.6535.4561911314.6943.1734711364.7346.9646211434.7839.30841
11544.8743.3669611614.92 36.550911644.9441.1526511704.9942.6765611740.6949.41242
#Mann= 3 , 0 , 0
9205.322    0.04       09205.322    0.04       011740.69    0.04       0
#XS Ineff= 2 , 0
       0 9738.28        10186.16       0
Bank Sta=9205.322,11740.69
Exp/Cntr=0.3,0.1

Type RM Length L Ch R = 1 ,7007.794,615.993200,615.993200,615.993200
XS GIS Cut Line= 2
873609.202216228 755512.32676349 872188.90268792753292.511840024
#Sta/Elev= 30
9126.31468.167919241.85857.801419277.47352.885589289.34547.278349503.03650.39008
9692.98346.466879752.34243.707489764.21439.473889783.52138.074969823.57224.56652
10001.6522.9928710037.2624.5225510061.0131.9006210072.8832.2328510203.4728.06698
 10274.730.8964510470.0427.7329510559.6230.4438110595.2327.9638810666.47 32.0662
10892.03 30.364510989.5734.4572411026.6831.2484711230.7830.4006211497.4932.79248
 11533.128.4189411556.8534.1220911604.3335.9603511657.5345.4092711761.6250.75456
#Mann= 3 , 0 , 0
9126.314  0.0457       09126.314  0.0457       011761.62  0.0457       0
#XS Ineff= 2 , 0
       09709.922         10080.8       0
Bank Sta=9126.314,11761.62
Exp/Cntr=0.3,0.1

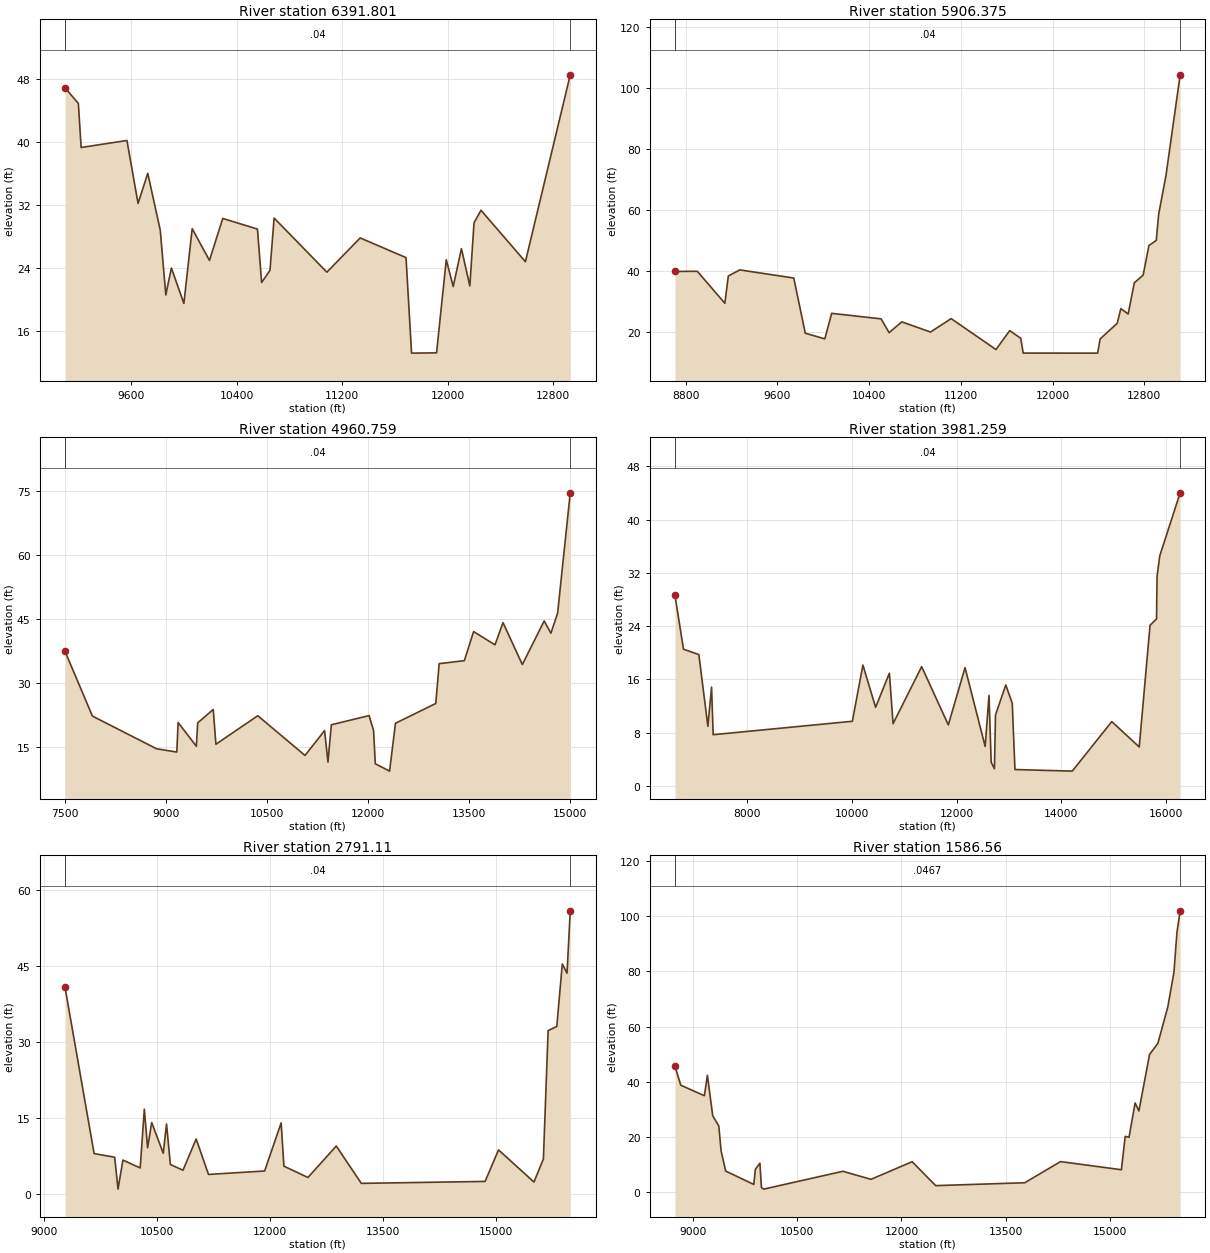
Type RM Length L Ch R = 1 ,6391.801,485.425800,485.425800,485.425800
XS GIS Cut Line= 2
873978.889562122755370.851538133 872775.88952764751732.017380295
#Sta/Elev= 30
9098.67146.889829199.625 44.8942 9220.69 39.29269568.25640.182119652.51532.17466
9726.24136.008479821.03228.751739863.16120.53145 9905.2923.9579910000.0819.44605
10063.2728.9630510194.24 24.918810294.9930.2618910558.2928.9081510589.8922.11204
10653.0823.6398710684.6830.3115911084.9123.4256711337.6827.7820111685.2525.27928
11727.3813.1233311916.9613.1583711990.6925.0084812043.3521.5980312105.7326.42019
12169.4421.67867 12201.329.69741   1225431.3030212591.0324.7597612931.2148.53813
#Mann= 3 , 0 , 0
9098.671    0.04       09098.671    0.04       012931.21    0.04       0
#XS Ineff= 2 , 0
       09765.207        10073.75       0
Bank Sta=9098.671,12931.21
Exp/Cntr=0.3,0.1

Type RM Length L Ch R = 1 ,5906.375,945.615800,945.615800,945.615800
XS GIS Cut Line= 3
874240.338259905755659.473985516874055.185288614752745.642692224
873544.097872154751349.229114755
#Sta/Elev= 30
8706.60439.84839 8901.47 39.90839141.95429.435479172.015  38.3689272.21640.36314
9743.16437.698649843.36619.6423710013.7117.7983210073.8326.14762 10504.7 24.3358
10574.8419.8206110685.0623.3633210935.5620.0256211115.9324.4194611506.71 14.2979
11626.8520.4903611722.8317.9822511744.1313.1407412393.7113.12333   1241517.74682
12564.0922.8846712596.0327.6715512659.9225.9320512713.17 36.115812790.6538.66936
12840.9548.3418312904.8449.9995612926.1458.6249112990.03 71.353913113.32104.2059
#Mann= 3 , 0 , 0
8706.604    0.04       08706.604    0.04       013113.32    0.04       0
#XS Ineff= 2 , 0
       09742.429        10090.31       0
Bank Sta=8706.604,13113.32
Exp/Cntr=0.3,0.1

Type RM Length L Ch R = 1 ,4960.759,979.499700,979.499700,979.499700
XS GIS Cut Line= 3
874911.368928527756850.447593021875227.142411064752616.179873141
873275.782802844750004.716877134
#Sta/Elev= 30
7501.57237.423217908.14522.241418860.78414.561949161.61713.780659181.67220.71741
9452.42215.145659472.47720.633689703.11623.782719743.22715.6240810364.9522.31487
11066.8912.99387 11357.718.8178711407.8411.4382811457.98 20.190312018.4822.34961
 12085.318.8490412111.0911.0393312323.319.30694412410.6920.5485113009.89 25.1967
13059.8334.5470413434.3335.2570313571.65 42.072813889.5838.9772414008.5644.18545
14295.6834.3425214620.2544.5768714720.1241.7000814819.9846.4271515007.5974.67154
#Mann= 3 , 0 , 0
7501.572    0.04       07501.572    0.04       015007.59    0.04       0
#XS Ineff= 2 , 0
       0 9666.33         10133.5       0
Bank Sta=7501.572,15007.59
Exp/Cntr=0.3,0.1

Type RM Length L Ch R = 1 ,3981.259,1190.149300,1190.149300,1190.149300
XS GIS Cut Line= 3
876560.628667373757767.016767222875701.752938238751971.937695486
874760.984192793 748297.73945484
#Sta/Elev= 30
6617.85828.614626781.64420.540727074.81219.734047246.6698.9622197317.43314.84345
7347.7617.70532210006.49 9.7186910208.67 18.1536 10451.311.8157610714.1416.93462
 10784.99.363477 11330.817.92203 11840.29.17597712159.7617.7734212543.785.947615
12617.5913.6087412658.883.56707512720.822.59367812741.4610.6669112937.5915.17565
13061.4612.4369213113.082.47424814207.272.23427214962.699.66899715487.275.865116
15693.7324.12686 15817.6 25.086815827.9231.4972515879.5334.5663616268.9644.02413
#Mann= 3 , 0 , 0
6617.858    0.04       06617.858    0.04       016268.96    0.04       0
#XS Ineff= 2 , 0
       09693.845        10155.14       0
Bank Sta=6617.858,16268.96
Exp/Cntr=0.3,0.1

Type RM Length L Ch R = 1 , 2791.11,1204.550400,1204.550400,1204.550400
XS GIS Cut Line= 3
877458.355425808754808.140140015876567.798895574752784.888955732
875255.603479872748484.039993358
#Sta/Elev= 30
9280.00240.793999665.8378.0552859938.9837.3321689983.3571.04831510048.246.770933
10277.685.22471410332.3116.7964610376.029.19792410430.6514.1685310583.618.122737
10627.3113.8769310678.385.89599610845.834.77343611020.6410.9236911184.533.945431
11929.574.62032412149.1314.1016312185.525.576384 12504.63.33941112880.989.537756
13213.542.18258614856.992.56711915034.738.77557915505.212.44195715630.676.992118
 15693.432.2762915808.4133.0976115881.5945.4113715944.3243.5921215987.1555.87972
#Mann= 3 , 0 , 0
9280.002    0.04       09280.002    0.04       015987.15    0.04       0
#XS Ineff= 2 , 0
       0                10333.73       0
Bank Sta=9280.002,15987.15
Exp/Cntr=0.3,0.1

Type RM Length L Ch R = 1 , 1586.56,1586.559600,1586.559600,1586.559600
XS GIS Cut Line= 2
878627.314562618754631.360971153875659.915497208747993.002945494
#Sta/Elev= 30
8740.01845.652578823.661 38.73839163.22334.922469207.03842.333029283.71327.63037
9371.34223.909119404.20314.901729469.9247.5931549875.2082.7234899897.1158.227176
9962.83710.443349984.7441.612909 10017.61.03219811156.787.50144611562.064.584667
12153.5610.9749712493.122.30003813774.693.34363914289.5111.01671 15165.88.068547
15220.5720.1875615275.3419.8180715362.9732.2867815417.7429.4000415571.0949.87245
15691.5853.9747315833.9767.14686 15921.679.6410215965.4294.1513316011.42101.9883
#Mann= 3 , 0 , 0
8740.018  0.0467       08740.018  0.0467       016011.42  0.0467       0
#XS Ineff= 2 , 0
       0                10485.46       0
Bank Sta=8740.018,16011.42
Exp/Cntr=0.3,0.1

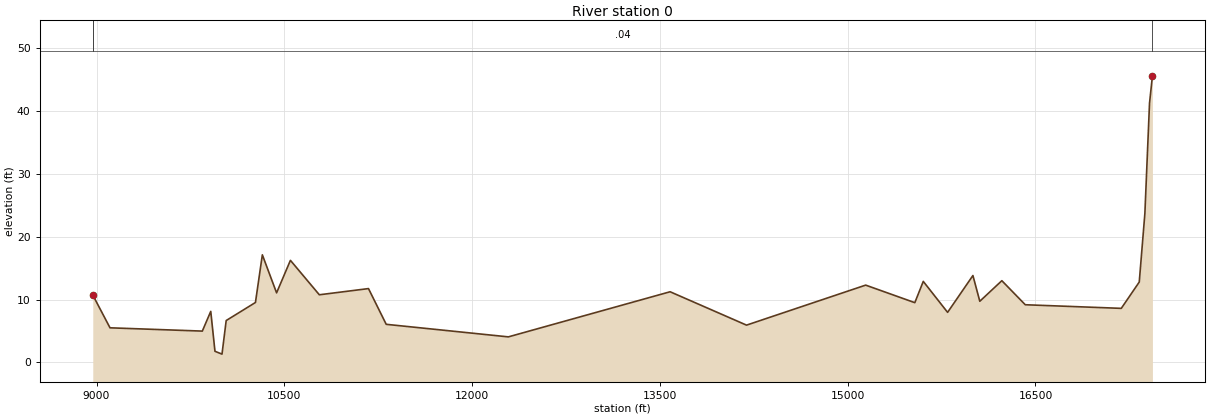
Type RM Length L Ch R = 1 ,       0,0.000000,0.000000,0.000000
XS GIS Cut Line= 6
879970.145332999753819.486026593879348.897892055751902.174885625
879896.788468195750072.956464402878959.729192688749899.019770587
878162.845361865749292.401982087876981.771827935747122.328143026
#Sta/Elev= 30
8969.84610.716799107.5965.4995449844.9314.9765959912.2778.1133229945.9491.766322
 10002.11.31387410035.626.65810510269.289.52742410324.4417.1092910438.1411.05984
10548.6216.23179 10779.610.75448 11172.311.7396811313.81 6.0545912289.584.057935
13581.6111.2349314191.955.925754 15143.712.2913615536.349.50016615603.8912.88414
15798.177.95897816000.3713.81752 16055.49.72275316231.4912.9964816418.599.169393
17185.578.59482917329.0712.7831717374.0523.7040417411.0741.2272917434.3145.58649
#Mann= 3 , 0 , 0
8969.846    0.04       08969.846    0.04       017434.31    0.04       0
#XS Ineff= 2 , 0
       0                10337.27       0
Bank Sta=8969.846,17434.31
Exp/Cntr=0.3,0.1